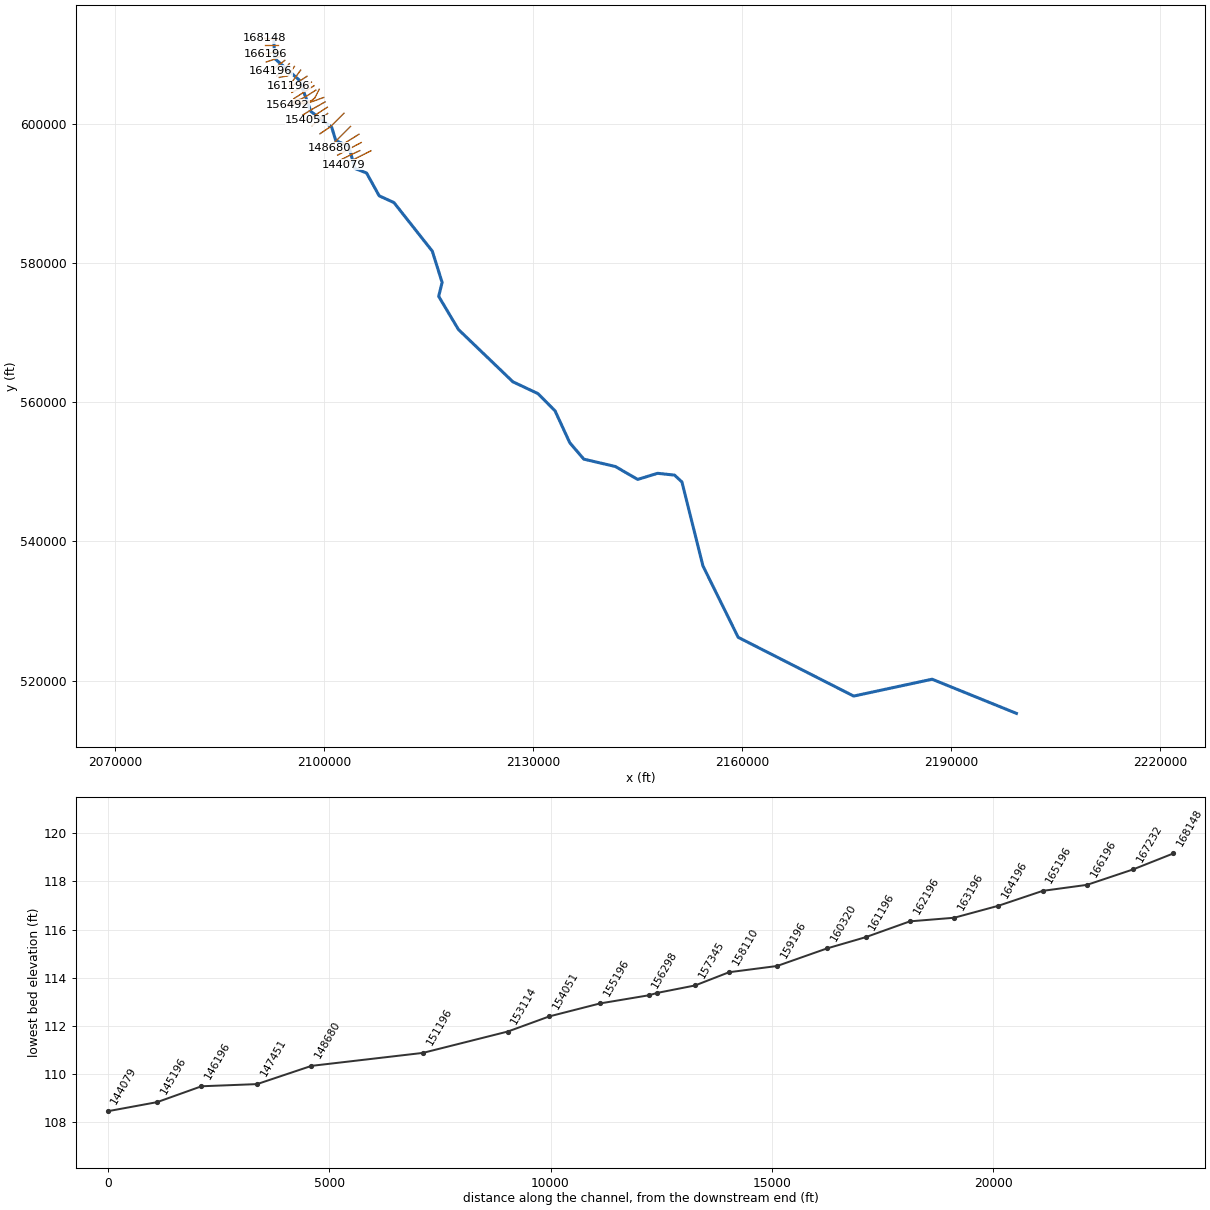
--- SCDOTFEMA.prj (project) ---

Proj Title=SCDOTFEMAFourHoleSwampLimitedDetailStudy
Current Plan=p02
Default Exp/Contr=0.3,0.1
English Units
Geom File=g01
Geom File=g02
Flow File=f01
Plan File=p01
Plan File=p02
Plan File=p03
Y Axis Title=Elevation
X Axis Title(PF)=Main Channel Distance
X Axis Title(XS)=Station
BEGIN DESCRIPTION:
Four Hole Swamp
END DESCRIPTION:
DSS Export Rating Curves= 0
DSS Export Rating Curve Sorted= 0
DSS Export Volume Flow Curves= 0
DXF Filename=..\FEMA Model\Four Hole Swamp\Four Hole Swamp.
DXF OffsetX= 0
DXF OffsetY= 0
DXF ScaleX= 1
DXF ScaleY= 10

--- SCDOTFEMA.p02 (plan) ---

Plan Title=SCDOT BR 100yr
Program Version=4.10
Short Identifier=SCDOTBR
Geom File=g02
Flow File=f01
Subcritical Flow
K Sum by GR= 0
Std Step Tol= 0.01
Critical Tol= 0.01
Num of Std Step Trials= 20
Max Error Tol= 0.3
Flow Tol Ratio= 0.001
Split Flow NTrial= 30
Split Flow Tol= 0.02
Split Flow Ratio= 0.02
Log Output Level= 0
Friction Slope Method= 1
Unsteady Friction Slope Method= 2
Unsteady Bridges Friction Slope Method= 1
Parabolic Critical Depth
Global Vel Dist= 0 , 0 , 0
Global Log Level= 0
CheckData=True
Encroach Param=-1 ,0,0, 0
BEGIN DESCRIPTION:
100Year Run SCDOT Design BR
END DESCRIPTION:
Computation Interval=1HOUR
Output Interval=1HOUR
Run HTab= 0
Run UNet= 0
Run PostProcess= 0
Run WQNet= 0
UNET Theta= 1
UNET Theta Warmup= 1
UNET ZTol= 0.02
UNET ZSATol= 0.05
UNET MxIter= 20
UNET MaxInSteps= 0
UNET DtIC= 0
UNET DtMin= 0
UNET MaxCRTS= 20
UNET WFStab= 2
UNET SFStab= 1
UNET WFX= 1
UNET SFX= 1
UNET DSS MLevel= 4
UNET DZMax Abort= 100
UNET Convert EG Bridges= 0
UNET Use Existing IB Tables=-1
UNET Froude Reduction=False
UNET Froude Limit= 1
UNET Froude Power= 10
UNET Time Slicing=0,0, 5
UNET Junction Losses=0
Instantaneous Interval=1HOUR
Write IC File= 0
Write IC File at Sim End=0
Echo Input=False
Echo Parameters=False
Echo Output=False
Write Detailed= 0
WQ AD Non Conservative
WQ ULTIMATE=-1
WQ Max Comp Step=1HOUR
WQ Output Interval=15MIN
WQ Output Selected Increments= 0
WQ Output face flow=0
WQ Output face velocity=0
WQ Output face area=0
WQ Output face dispersion=0
WQ Output cell volume=0
WQ Output cell surface area=0
WQ Output cell continuity=0
WQ Output cumulative cell continuity=0
WQ Output face conc=0
WQ Output face dconc_dx=0
WQ Output face courant=0
WQ Output face peclet=0
WQ Output face adv mass=0
WQ Output face disp mass=0
WQ Output cell mass=0
WQ Output cell source sink temp=0
WQ Output cell source sink nsm=0
WQ Output MaxMinRange=-1
WQ Daily Max Min Mean=-1
WQ Daily Range=0
WQ Daily Time=0
WQ Create Restart=0
WQ Fixed Restart=0
WQ System Summary=0
WQ Use Fixed Temperature=0
Sorting and Armoring Iterations= 10
XS Update Threshold= 0.02
Hydraulics Update Threshold= 0.02
Energy Slope Method= 1
Volume Change Method= 0
XS Weighting Method= 0
Number of US Weighted Cross Sections= 1
Number of DS Weighted Cross Sections= 1
Upstream XS Weight=0.25
Main XS Weight=0.5
Downstream XS Weight=0.25
Number of DS XS's Weighted with US Boundary= 1
Upstream Boundary Weight= 1
Weight of XSs Associated with US Boundary= 0
Number of US XS's Weighted with DS Boundary= 1
Downstream Boundary Weight= 0.5
Weight of XSs Associated with DS Boundary= 0.5
Sediment Output Level= 4
Mass or Volume Output= 0
Output Increment Type= 1
Profile and TS Output Increment= 10
XS Output Flag= 0
XS Output Increment= 10
Disregard all LS=0
Disregard all Conn=0
Disregard all Breaches=0
Disregard all Pumps=0

--- SCDOTFEMA.p01 (plan) ---

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Plan Title=100-Year Single
Short Identifier=100Year
Geom File=g01
Flow File=f01
Encroach Param= -1, 0, 0, 0
100Year Run

--- SCDOTFEMA.p03 (plan) ---

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Plan Title=FEMA Existing
Short Identifier=Existing
Geom File=g01
Flow File=f01
100Year Run

--- SCDOTFEMA.f01 (steady flow) ---

Flow Title=100-year Single
Number of Profiles=1
Profile Names=100-year
River Rch & RM= Four Hole Swamp,Reach-1,168148
    3621
River Rch & RM= Four Hole Swamp,Reach-1,161196
    5245
River Rch & RM= Four Hole Swamp,Reach-1,148680
    6261
River Rch & RM= Four Hole Swamp,Reach-1,146196
    6755
River Rch & RM= Four Hole Swamp,Reach-1,141196
    6885
River Rch & RM= Four Hole Swamp,Reach-1,138150
    7050
River Rch & RM= Four Hole Swamp,Reach-1,136196
    7116
River Rch & RM= Four Hole Swamp,Reach-1,125984
    7666
River Rch & RM= Four Hole Swamp,Reach-1,116196
    8061
River Rch & RM= Four Hole Swamp,Reach-1,107196
    8330
River Rch & RM= Four Hole Swamp,Reach-1,101196
    8359
River Rch & RM= Four Hole Swamp,Reach-1,100196
    8476
River Rch & RM= Four Hole Swamp,Reach-1,94196
    8539
River Rch & RM= Four Hole Swamp,Reach-1,82196
   10331
River Rch & RM= Four Hole Swamp,Reach-1,77686
   10390
River Rch & RM= Four Hole Swamp,Reach-1,68220
   11812
River Rch & RM= Four Hole Swamp,Reach-1,66334
   11919
Boundary for River Rch & Prof#=Four Hole Swamp,Reach-1,1
Up Type=0
Dn Type=1
Dn Known WS=82.22

--- SCDOTFEMA.g02 (geometry) ---

Geom Title=Proposed Conditions
Program Version=4.10

River Reach=Four Hole Swamp ,Reach-1
Reach XY= 30
       2092765.4       612281.68      2092902.25       609383.32
      2096465.32       606253.41      2098098.33       601775.09
      2101090.37       599502.18      2101663.93       597603.88
      2103550.64       596752.27      2104403.81       593588.06
      2106081.44       592944.04      2107901.88       589658.29
      2110014.04       588690.83      2115523.43       581709.44
      2116931.48       577213.63      2116438.55        575219.7
      2119272.79       570453.98      2127092.85       562939.18
      2130691.21       561243.57      2133142.27       558768.62
      2135250.72       554191.93      2137267.87       551832.06
      2141797.46       550773.36      2144996.38       548917.91
      2147860.38       549795.26      2150286.73       549537.36
      2151349.12       548556.27      2154370.61       536484.92
      2159426.71       526234.08      2176005.83       517793.65
      2187259.74       520215.68      2199359.79       515309.29

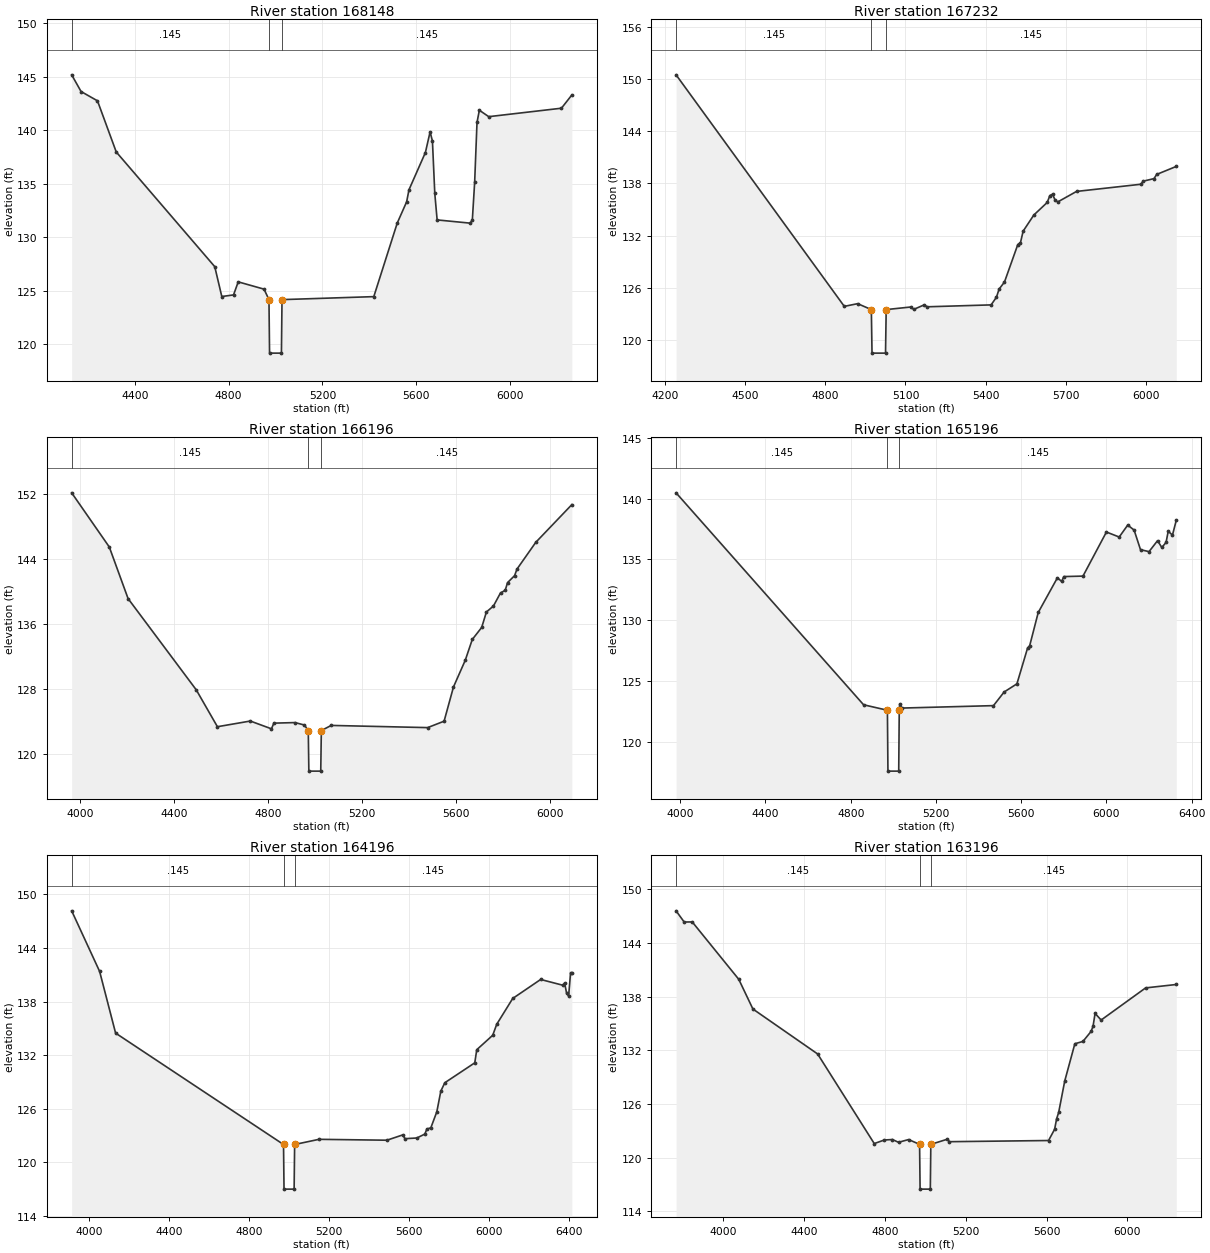
Type RM Length L Ch R = 1 ,168148  ,916,916,916
BEGIN DESCRIPTION:
Four Hole Swamp 186.0
END DESCRIPTION:
XS GIS Cut Line= 3
      2093606.67       612105.04      2092741.32       612173.41
      2091480.89       612272.99
#Sta/Elev= 30
  4131.1  145.18  4171.1  143.62  4241.1  142.75  4321.1  137.97  4741.1  127.25
  4771.1  124.46  4821.1  124.61  4841.1  125.83  4951.1  125.15  4972.2  124.17
  4974.7  119.17  5025.3  119.17  5027.8  124.17  5419.1  124.45  5519.1  131.33
  5559.1  133.31  5569.1  134.44  5639.1  137.92  5659.1  139.85  5669.1  138.99
  5679.1   134.1  5689.1  131.62  5829.1  131.32  5839.1  131.58  5849.1  135.15
  5859.1  140.73  5869.1  141.87  5909.1  141.27  6219.1  142.06  6263.5   143.3
#Mann= 3 ,-1 , 0
  4131.1    .145       0  4972.2     .05       0  5027.8    .145       0
Bank Sta=4972.2,5027.8
XS Rating Curve= 0 ,0
Exp/Cntr=0.3,0.1

Type RM Length L Ch R = 1 ,167232  ,1036,1036,1036
BEGIN DESCRIPTION:
Four Hole Swamp 185.0
END DESCRIPTION:
XS GIS Cut Line= 3
      2093417.28       611262.37      2092657.46       611262.37
      2091544.08       611262.37
#Sta/Elev= 30
  4240.9  150.46  4870.9  123.87  4920.9  124.18  4972.2   123.5  4974.7   118.5
  5025.3   118.5  5027.8   123.5  5120.7   123.8  5130.7  123.52  5170.7  124.05
  5180.7  123.82  5420.7  124.04  5440.7  124.92  5450.7  125.86  5470.7  126.66
  5520.7  130.97  5530.7  131.19  5540.7  132.51  5580.7  134.36  5630.7   135.8
  5640.7  136.59  5650.7  136.75  5660.7  136.05  5670.7  135.87  5740.7  137.07
  5980.7  137.89  5990.7  138.25  6030.7  138.54  6040.7  139.02  6114.1  139.94
#Mann= 3 ,-1 , 0
  4240.9    .145       0  4972.2     .05       0  5027.8    .145       0
Bank Sta=4972.2,5027.8
XS Rating Curve= 0 ,0
Exp/Cntr=0.3,0.1

Type RM Length L Ch R = 1 ,166196  ,1000,1000,1000
BEGIN DESCRIPTION:
Four Hole Swamp 184.0
END DESCRIPTION:
XS GIS Cut Line= 3
      2093659.99       610397.02      2092639.62       610227.85
      2091559.92       610054.05
#Sta/Elev= 30
  3965.7  152.14  4125.7  145.47  4205.7  139.11  4495.7  127.87  4585.7  123.33
  4725.7  124.03  4815.7  123.07  4825.7  123.77  4915.7  123.84  4955.7  123.54
  4972.2  122.86  4974.7  117.86  5025.3  117.86  5027.8  122.86    5070  123.49
    5480  123.22    5550  124.01    5590  128.23    5640  131.51    5670  134.08
    5710  135.56    5730  137.46    5760   138.2    5790  139.81    5810  140.13
    5820  141.08    5850  141.94    5860  142.74    5940  146.04  6093.6  150.69
#Mann= 3 ,-1 , 0
  3965.7    .145       0  4972.2     .05       0  5027.8    .145       0
Bank Sta=4972.2,5027.8
XS Rating Curve= 0 ,0
Exp/Cntr=0.3,0.1

Type RM Length L Ch R = 1 ,165196  ,1000,1000,1000
BEGIN DESCRIPTION:
Four Hole Swamp 183.0
END DESCRIPTION:
XS GIS Cut Line= 3
      2093839.37       609806.05      2092957.81       609293.76
      2091691.72       608893.68
#Sta/Elev= 30
  3980.4  140.47  4860.4  123.06  4972.2  122.61  4974.7  117.61  5025.3  117.61
  5027.8  122.61    5030  123.12    5040  122.79    5470  122.99    5520  124.11
    5580  124.78    5630  127.72    5640  127.92    5680  130.64    5770  133.49
    5790  133.19    5800  133.59    5890  133.63    6000  137.25    6060  136.84
    6100  137.82    6130  137.41    6160   135.8    6200  135.64    6240  136.54
    6260  135.98    6280   136.4    6290  137.31    6310     137  6327.8  138.21
#Mann= 3 ,-1 , 0
  3980.4    .145       0  4972.2     .05       0  5027.8    .145       0
Bank Sta=4972.2,5027.8
XS Rating Curve= 0 ,0
Exp/Cntr=0.3,0.1

Type RM Length L Ch R = 1 ,164196  ,1000,1000,1000
BEGIN DESCRIPTION:
Four Hole Swamp 182.0
END DESCRIPTION:
XS GIS Cut Line= 3
      2094352.51       609119.11      2093492.21       608451.76
       2092340.9       607626.89
#Sta/Elev= 30
  3911.2  148.17  4051.2  141.38  4131.2  134.47  4972.2  121.99  4974.7  116.99
  5025.3  116.99  5027.8  121.99    5150  122.57    5490  122.47    5570  123.07
    5580  122.64    5640  122.72    5680  123.16    5690  123.72    5710  123.86
    5740  125.66    5760  127.97    5780  128.91    5930  131.14    5940  132.61
    6020  134.23    6040  135.46    6120  138.35    6260  140.48    6370  139.84
    6380  140.08    6390  138.93    6400  138.63    6410  141.24  6416.3  141.22
#Mann= 3 ,-1 , 0
  3911.2    .145       0  4972.2     .05       0  5027.8    .145       0
Bank Sta=4972.2,5027.8
XS Rating Curve= 0 ,0
Exp/Cntr=0.3,0.1

Type RM Length L Ch R = 1 ,163196  ,1000,1000,1000
BEGIN DESCRIPTION:
Four Hole Swamp 181.0
END DESCRIPTION:
XS GIS Cut Line= 3
      2095003.85       608640.96       2094175.4       607729.09
      2093214.81        606942.6
#Sta/Elev= 30
    3768  147.58    3808  146.33    3848  146.34    4078  139.93    4148  136.61
    4468  131.59    4748  121.58    4798  121.98    4838  122.03    4868  121.72
    4918  122.03  4972.2  121.49  4974.7  116.49  5025.3  116.49  5027.8  121.49
    5110  122.07    5120  121.79    5610  121.92    5640  123.18    5650  124.36
    5660  125.06    5690  128.57    5740  132.73    5780  132.99    5820   134.1
    5830  134.68    5840  136.12    5870  135.38    6090  138.97  6241.5  139.35
#Mann= 3 ,-1 , 0
    3768    .145       0  4972.2     .05       0  5027.8    .145       0
Bank Sta=4972.2,5027.8
XS Rating Curve= 0 ,0
Exp/Cntr=0.3,0.1

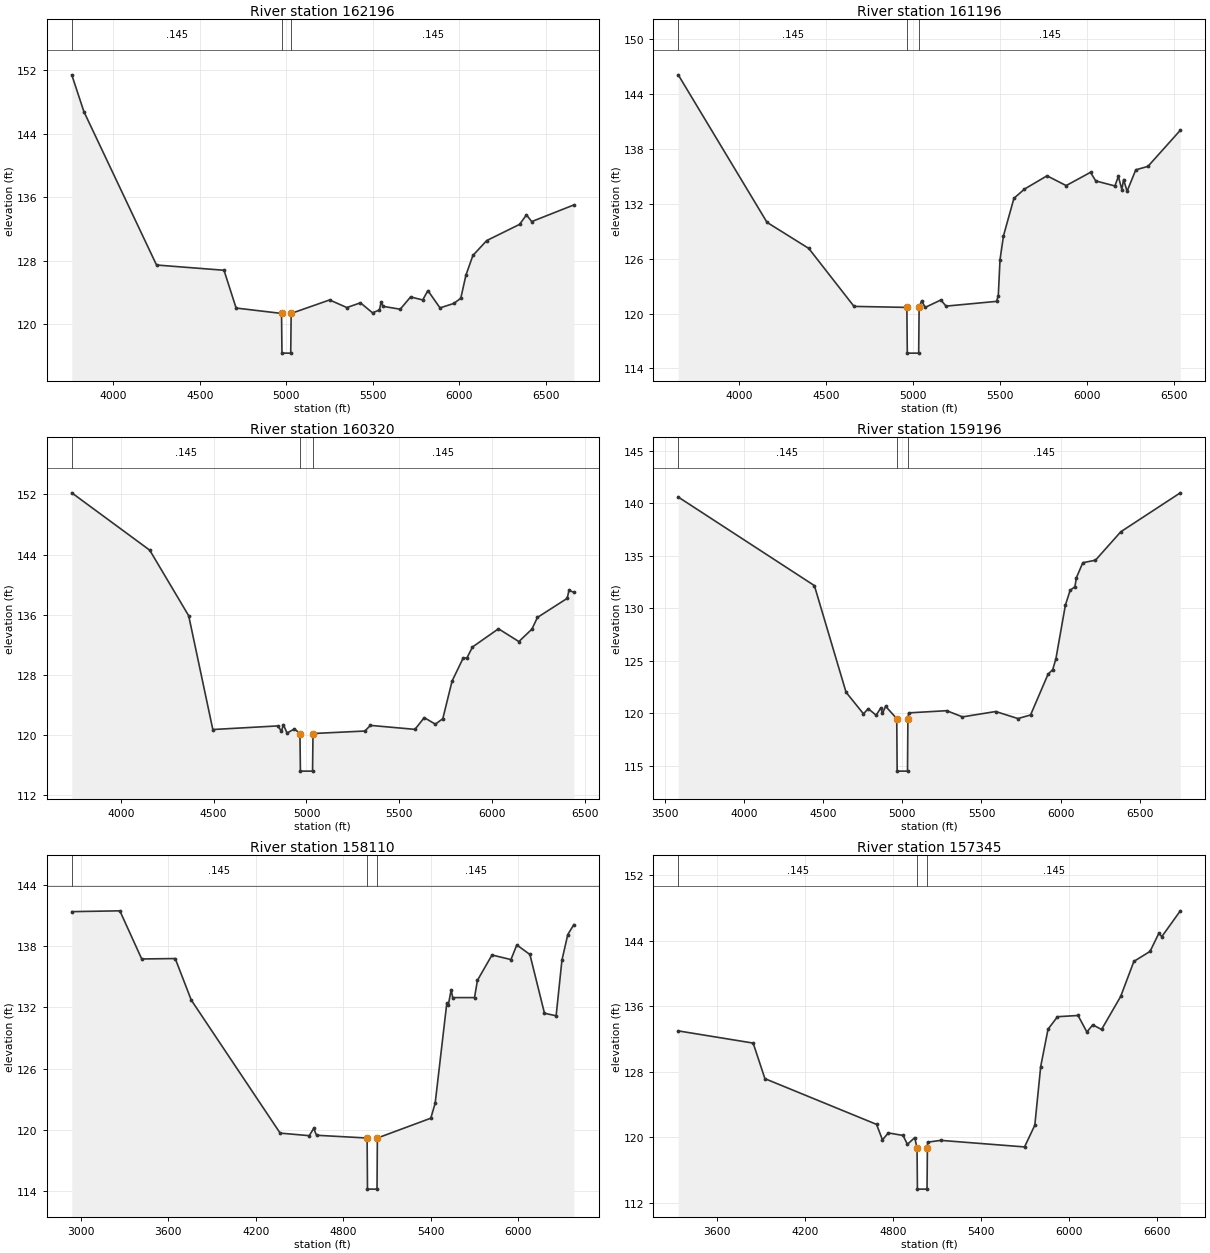
Type RM Length L Ch R = 1 ,162196  ,1000,1000,1000
BEGIN DESCRIPTION:
Four Hole Swamp 180.0
END DESCRIPTION:
XS GIS Cut Line= 4
       2095737.6       608253.45      2095040.49       607227.48
        2094773.       606893.11      2093561.08       606662.27
#Sta/Elev= 30
  3759.6   151.4  3829.6  146.77  4249.6  127.44  4639.6  126.78  4709.6  122.02
  4972.2  121.34  4974.7  116.34  5025.3  116.34  5027.8  121.34    5250  123.04
    5350  122.08  5428.2  122.68  5498.2  121.42  5538.2  121.78  5548.2  122.82
  5558.2  122.24  5658.2  121.87  5718.2  123.42  5788.2  123.04  5818.2  124.22
  5888.2  122.04  5968.2   122.6  6008.2  123.25  6038.2  126.17  6078.2  128.64
  6158.2  130.52  6348.2  132.56  6388.2  133.76  6418.2  132.91  6661.9  135.01
#Mann= 3 ,-1 , 0
  3759.6    .145       0  4972.2     .05       0  5027.8    .145       0
Bank Sta=4972.2,5027.8
XS Rating Curve= 0 ,0
Exp/Cntr=0.3,0.1

Type RM Length L Ch R = 1 ,161196  ,876,876,876
BEGIN DESCRIPTION:
Four Hole Swamp 179.0
END DESCRIPTION:
XS GIS Cut Line= 3
      2096632.61       607716.35      2095834.42       606629.08
      2094943.48         605378.
#Sta/Elev= 30
  3651.2  146.11  4161.2  129.98  4401.2  127.13  4661.2  120.79  4964.8  120.68
  4967.3  115.68  5032.7  115.68  5035.2  120.68    5050   121.4    5070  120.68
    5160  121.49    5190  120.82    5480  121.34    5490  121.93    5500  125.89
    5520  128.51    5580  132.61    5640  133.61    5770  135.07    5880     134
    6020  135.45    6050  134.51    6160  133.96    6180     135    6200  133.57
    6210  134.66    6230  133.38    6280  135.72    6350   136.1  6535.9  140.05
#Mann= 3 ,-1 , 0
  3651.2    .145       0  4964.8     .05       0  5035.2    .145       0
Bank Sta=4964.8,5035.2
XS Rating Curve= 0 ,0
Exp/Cntr=0.3,0.1

Type RM Length L Ch R = 1 ,160320  ,1124,1124,1124
BEGIN DESCRIPTION:
Four Hole Swamp 178.0
END DESCRIPTION:
XS GIS Cut Line= 3
      2097534.88       606827.14      2096470.34       606136.19
      2095265.76       605354.33
#Sta/Elev= 30
  3735.4   152.2  4155.4  144.58  4365.4  135.86  4495.4  120.74  4845.4  121.22
  4865.4  120.51  4875.4  121.39  4895.4  120.27  4935.4  120.82  4964.8  120.21
  4967.3  115.21  5032.7  115.21  5035.2  120.21  5314.5  120.54  5344.5  121.29
  5584.5  120.76  5634.5  122.32  5694.5  121.45  5734.5  122.18  5784.5  127.18
  5844.5  130.25  5864.5  130.25  5894.5  131.71  6034.5  134.13  6144.5  132.43
  6214.5  134.08  6244.5  135.64  6404.5  138.17  6414.5  139.23  6440.6  138.98
#Mann= 3 ,-1 , 0
  3735.4    .145       0  4964.8     .05       0  5035.2    .145       0
Bank Sta=4964.8,5035.2
XS Rating Curve= 0 ,0
Exp/Cntr=0.3,0.1

Type RM Length L Ch R = 1 ,159196  ,1086,1086,1086
BEGIN DESCRIPTION:
Four Hole Swamp 177.0
END DESCRIPTION:
XS GIS Cut Line= 3
      2098177.67       606005.67      2096955.81       605291.03
       2095376.5       604523.59
#Sta/Elev= 30
  3584.5   140.6  4444.5  132.16  4644.5     122  4754.5  119.94  4784.5  120.43
  4834.5  119.81  4864.5  120.51  4874.5  119.98  4894.5  120.66  4964.8  119.48
  4967.3  114.48  5032.7  114.48  5035.2  119.48    5040  120.03    5280  120.24
    5380  119.65    5590  120.16    5730  119.49    5810  119.83    5920   123.7
    5950  124.16    5970  125.18    6030   130.3    6060  131.71    6090  132.05
    6100  132.93    6140  134.34    6220  134.58    6380  137.29  6755.9     141
#Mann= 3 ,-1 , 0
  3584.5    .145       0  4964.8     .05       0  5035.2    .145       0
Bank Sta=4964.8,5035.2
XS Rating Curve= 0 ,0
Exp/Cntr=0.3,0.1

Type RM Length L Ch R = 1 ,158110  ,765,765,765
BEGIN DESCRIPTION:
Four Hole Swamp 176.0
END DESCRIPTION:
XS GIS Cut Line= 3
      2098540.06       605470.35      2096802.04       604357.03
      2095638.68       603611.81
#Sta/Elev= 30
  2937.9  141.37  3267.9  141.45  3417.9  136.74  3647.9  136.78  3757.9  132.72
  4367.9   119.7  4567.9  119.45  4597.9  120.16  4617.9  119.49  4964.8  119.22
  4967.3  114.22  5032.7  114.22  5035.2  119.22  5401.9  121.16  5431.9  122.64
  5511.9  132.45  5521.9  132.24  5541.9  133.73  5551.9  132.96  5701.9  132.96
  5721.9  134.65  5821.9  137.13  5951.9  136.68  5991.9  138.11  6081.9  137.18
  6181.9  131.43  6261.9  131.18  6301.9  136.63  6341.9  139.13  6383.5   140.1
#Mann= 3 ,-1 , 0
  2937.9    .145       0  4964.8     .05       0  5035.2    .145       0
Bank Sta=4964.8,5035.2
XS Rating Curve= 0 ,0
Exp/Cntr=0.3,0.1

Type RM Length L Ch R = 1 ,157345  ,853,853,853
BEGIN DESCRIPTION:
Four Hole Swamp 175.0
END DESCRIPTION:
XS GIS Cut Line= 4
      2098820.29       604848.78      2097408.89       603942.96
      2096608.41       603522.14      2095782.89       603390.36
#Sta/Elev= 30
  3339.3  132.98  3849.3  131.49  3929.3  127.15  4689.3  121.57  4729.3  119.68
  4769.3  120.53  4869.3  120.22  4899.3  119.14  4949.3  119.96  4964.8  118.67
  4967.3  113.67  5032.7  113.67  5035.2  118.67  5036.4   119.4  5126.4  119.62
  5696.4  118.82  5766.4  121.47  5806.4  128.63  5856.4  133.19  5920.7  134.71
  6060.7  134.86  6120.7  132.84  6160.7  133.72  6220.7  133.15  6350.7  137.18
  6440.7  141.46  6550.7  142.68  6610.7  144.89  6630.7  144.48  6756.7  147.63
#Mann= 3 ,-1 , 0
  3339.3    .145       0  4964.8     .05       0  5035.2    .145       0
Bank Sta=4964.8,5035.2
XS Rating Curve= 0 ,0
Exp/Cntr=0.5,0.3

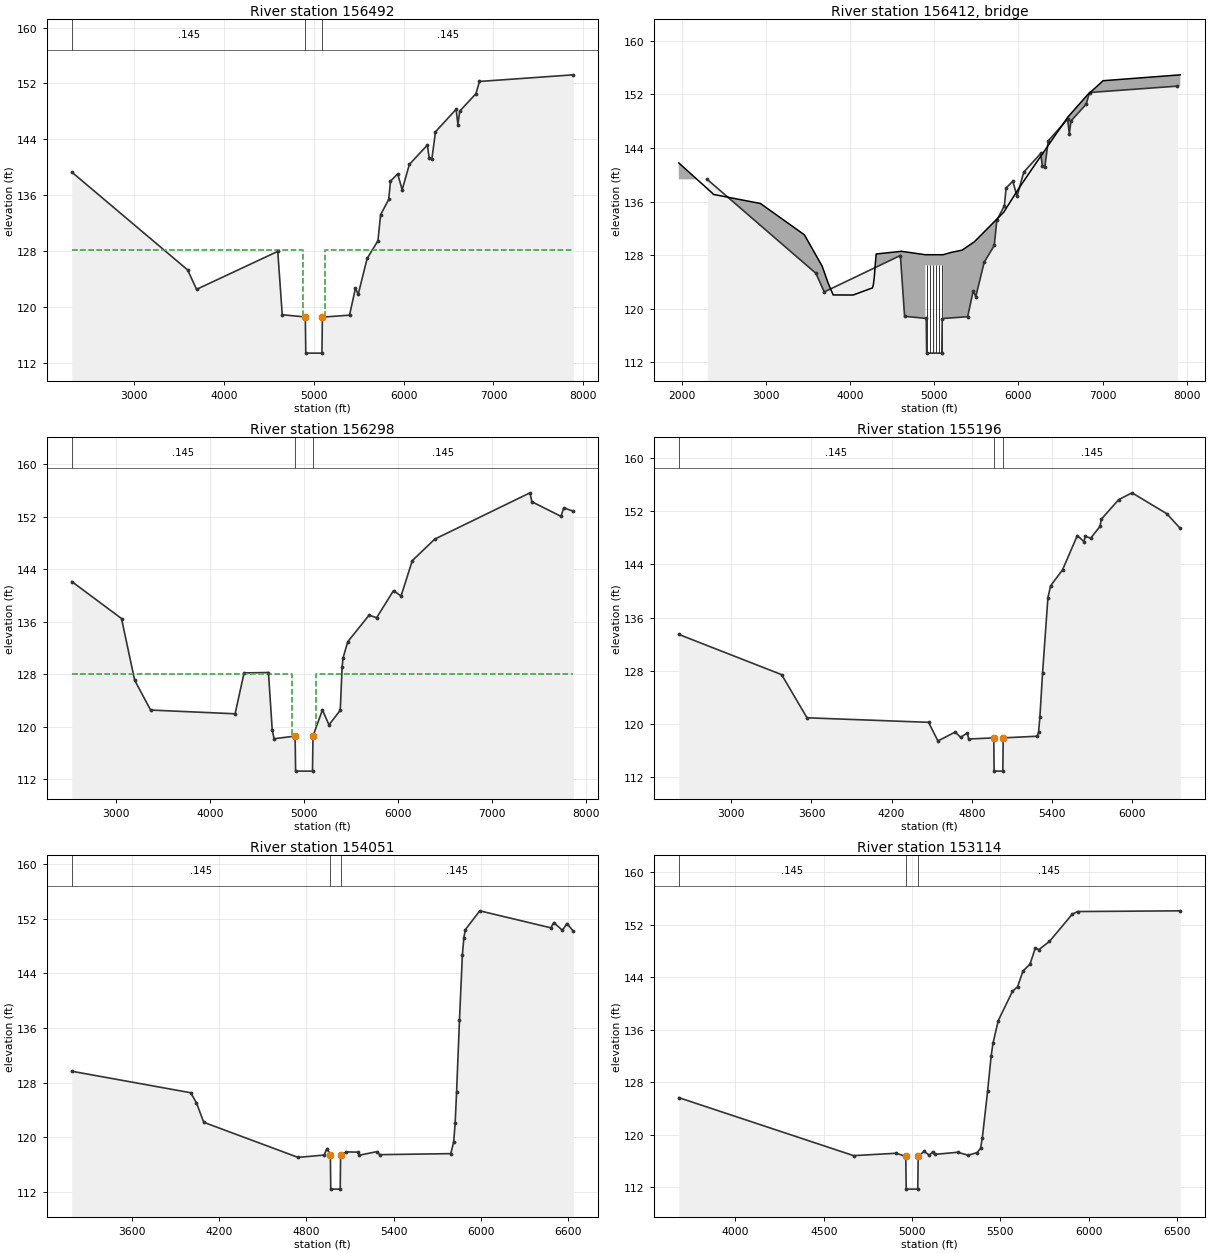
Type RM Length L Ch R = 1 ,156492  ,194,194,194
BEGIN DESCRIPTION:
Four Hole Road - US
END DESCRIPTION:
XS GIS Cut Line= 6
      2099292.43       604967.16      2098667.55       603725.18
      2098211.19       603361.06      2097529.38       603131.91
      2095689.79       603175.34      2094750.94       602731.06
#Sta/Elev= 30
  2303.8  139.31  3593.8  125.29  3694.1   122.5  4597.9  127.94  4647.9  118.86
    4905  118.54    4910  113.36    5090  113.36    5095  118.52  5397.2   118.8
  5463.4  122.67  5493.4  121.77  5593.4  126.93  5713.4  129.45  5743.4   133.2
  5833.4  135.38  5853.4  138.01  5933.4  139.05  5983.4  136.76  6063.4   140.4
  6264.4  143.18  6284.4  141.28  6314.4   141.2  6354.4  145.07  6584.4  148.31
  6604.4  146.09  6624.4  148.04  6804.4  150.53  6844.4  152.29  7889.2  153.24
#Mann= 3 ,-1 , 0
  2303.8    .145       0    4905     .05       0    5095    .145       0
#XS Ineff= 2 , 0
       0  4878.9  128.11  5121.1       0  128.11
Permanent Ineff=
       F       F
Bank Sta=4905,5095
XS Rating Curve= 0 ,0
Exp/Cntr=0.5,0.3

Type RM Length L Ch R = 3 ,156412  ,,,
BEGIN DESCRIPTION:
Four Hole Road - TOR
Structure ID: LDS_FHS_08
Approximate Survey Structure
END DESCRIPTION:
Bridge Culvert--1,0,-1,-1, 0
Deck Dist Width WeirC Skew NumUp NumDn MinLoCord MaxHiCord MaxSubmerge Is_Ogee
62,36,3,0, 31, 31, , , 0.95, 0, 1,1,,
  1965.9  2365.9  2375.9  2935.9    3458    3668  3739.7  3799.7  4037.2  4267.2
  4277.2  4287.2  4290.4  4300.4  4310.4  4610.4    4894    4894    5106    5106
  5202.8  5331.2  5477.2  5825.4  6003.5  6182.6  6418.7  6584.8    6818  7005.4
    7923
  141.77  137.24  137.07  135.71  131.03  126.37  123.83  122.05  122.04  123.11
   123.6  124.61  125.05  126.78  128.17  128.57  128.06  128.06  128.06  128.06
  128.41  128.74     130  134.41  137.95  141.26  145.57  148.59  151.91  154.05
  154.93
   95.16   95.16   95.16   95.16   95.16   95.16   95.16   95.16   95.16   95.16
   95.16   95.16   95.16   95.16   95.16   95.16   95.16  126.46  126.46   95.16
   95.16   95.16   95.16   95.16   95.16   95.16   95.16   95.16   95.16   95.16
   95.16
  1965.9  2365.9  2375.9  2935.9    3458    3668  3739.7  3799.7  4037.2  4267.2
  4277.2  4287.2  4290.4  4300.4  4310.4  4610.4    4894    4894    5106    5106
  5202.8  5331.2  5477.2  5825.4  6003.5  6182.6  6418.7  6584.8    6818  7005.4
    7923
  141.77  137.24  137.07  135.71  131.03  126.37  123.83  122.05  122.04  123.11
   123.6  124.61  125.05  126.78  128.17  128.57  128.06  128.06  128.06  128.06
  128.41  128.74     130  134.41  137.95  141.26  145.57  148.59  151.91  154.05
  154.93
   95.16   95.16   95.16   95.16   95.16   95.16   95.16   95.16   95.16   95.16
   95.16   95.16   95.16   95.16   95.16   95.16   95.16  126.46  126.46   95.16
   95.16   95.16   95.16   95.16   95.16   95.16   95.16   95.16   95.16   95.16
   95.16
Pier Skew, UpSta & Num, DnSta & Num=  ,4911.7, 2 ,4911.7, 2 , 0 , 0 , 0 ,0,0
       1       1
  115.16  126.46
       1       1
  114.91  126.46
Pier Skew, UpSta & Num, DnSta & Num=  ,4947, 2 ,4947, 2 , 0 , 0 , 0 ,0,0
       1       1
  115.16  126.46
       1       1
  114.91  126.46
Pier Skew, UpSta & Num, DnSta & Num=  ,4982.3, 2 ,4982.3, 2 , 0 , 0 , 0 ,0,0
       1       1
  115.16  126.46
       1       1
  114.91  126.46
Pier Skew, UpSta & Num, DnSta & Num=  ,5017.7, 2 ,5017.7, 2 , 0 , 0 , 0 ,0,0
       1       1
  115.16  126.46
       1       1
  114.91  126.46
Pier Skew, UpSta & Num, DnSta & Num=  ,5053, 2 ,5053, 2 , 0 , 0 , 0 ,0,0
       1       1
  115.16  126.46
       1       1
  114.91  126.46
Pier Skew, UpSta & Num, DnSta & Num=  ,5088.3, 2 ,5088.3, 2 , 0 , 0 , 0 ,0,0
       1       1
  115.16  126.46
       1       1
  114.91  126.46
Abutment Skew #Up #Dn= , 2 , 2
    4894    4910
  126.46  115.16
    4894    4910
  126.46  114.91
Abutment Skew #Up #Dn= , 2 , 2
    5090    5106
  115.16  126.46
    5090    5106
  114.91  126.46
BR Coef= 1 , 1 , 0 ,1.25, 0 ,,,0.8,0,2,0,
WSPro=,,,, 1 ,,,, 0 ,,,, 0 ,,,,-1 ,-1 ,-1 , 0 , 0 , 0 , 0 , 0
BC Design=,, 0 ,, 0 ,,,,,,
BC HTab HWMax=153.3
BC Use User HTab Curves=0
BC User HTab FreeFlow(D)= 0

Type RM Length L Ch R = 1 ,156298  ,1102,1102,1102
BEGIN DESCRIPTION:
Four Hole Road - DS
END DESCRIPTION:
XS GIS Cut Line= 6
      2099944.05       603787.29      2097620.27       602960.47
      2097081.33       602865.18      2096461.01       602965.77
      2095857.45       602928.05      2094864.13        602475.4
#Sta/Elev= 30
  2525.8  142.16  3055.8  136.52  3195.8  127.12  3365.8  122.57  4265.8     122
  4360.9  128.23  4620.9  128.29  4660.9  119.56  4680.9   118.2    4905   118.6
    4910  113.26    5090  113.26    5095   118.6  5195.6  122.58  5265.6  120.32
  5385.6  122.53  5405.6   129.2  5415.6  130.53  5465.6  132.99  5692.9  137.04
  5772.9  136.64  5952.9  140.78  6032.9  139.95  6152.9  145.34  6391.4  148.62
  7406.1  155.68  7426.1  154.32  7736.1   152.1  7766.1   153.4  7867.7  152.87
#Mann= 3 ,-1 , 0
  2525.8    .145       0    4905     .05       0    5095    .145       0
#XS Ineff= 2 , 0
       0  4870.4  128.09  5129.6       0  128.09
Permanent Ineff=
       F       F
Bank Sta=4905,5095
XS Rating Curve= 0 ,0
Exp/Cntr=0.5,0.3

Type RM Length L Ch R = 1 ,155196  ,1145,1145,1145
BEGIN DESCRIPTION:
Four Hole Swamp 173.0
END DESCRIPTION:
XS GIS Cut Line= 3
      2100144.08        603154.6      2098062.18        601973.9
      2096910.91       601247.27
#Sta/Elev= 30
  2606.6  133.48  3376.6  127.43  3566.6  120.94  4476.6  120.26  4546.6  117.46
  4676.6   118.8  4716.6     118  4766.6  118.67  4776.6  117.75  4964.8  117.92
  4967.3  112.92  5032.7  112.92  5035.2  117.92    5290  118.17    5300  118.77
    5310  121.07    5330  127.68    5370  138.99    5390  140.78    5480  143.21
    5590  148.34    5640  147.44    5650  148.27    5690  147.94    5760  149.73
    5770  150.81    5900  153.75    6000  154.77    6260  151.63  6361.4  149.41
#Mann= 3 ,-1 , 0
  2606.6    .145       0  4964.8     .05       0  5035.2    .145       0
Bank Sta=4964.8,5035.2
XS Rating Curve= 0 ,0
Exp/Cntr=0.3,0.1

Type RM Length L Ch R = 1 ,154051  ,937,937,937
BEGIN DESCRIPTION:
Four Hole Swamp 172.0
END DESCRIPTION:
XS GIS Cut Line= 3
      2100456.13       602384.98      2098927.27       601391.86
      2097556.41       600501.36
#Sta/Elev= 30
  3181.7  129.65  4001.7   126.5  4041.7  125.01  4091.7  122.17  4741.7  117.03
  4921.7  117.37  4941.7  118.33  4964.8  117.38  4967.3  112.38  5032.7  112.38
  5035.2  117.38  5074.8  117.83  5154.8   117.8  5164.8  117.35  5284.8  117.87
  5304.8  117.43  5794.8  117.58  5814.8   119.3  5824.8  122.01  5834.8   126.6
  5854.8  137.16  5874.8  146.71  5884.8  149.16  5894.8  150.39  5994.8  153.15
  6484.8  150.66  6504.8  151.43  6564.8  150.29  6594.8  151.29  6639.5  150.18
#Mann= 3 ,-1 , 0
  3181.7    .145       0  4964.8     .05       0  5035.2    .145       0
Bank Sta=4964.8,5035.2
XS Rating Curve= 0 ,0
Exp/Cntr=0.3,0.1

Type RM Length L Ch R = 1 ,153114  ,1918,1918,1918
BEGIN DESCRIPTION:
Four Hole Swamp 171.0
END DESCRIPTION:
XS GIS Cut Line= 3
      2100506.26       601489.03      2099448.56       600667.09
      2098263.05       599745.84
#Sta/Elev= 30
  3679.1  125.68  4669.1  116.85  4909.1  117.21  4964.8  116.75  4967.3  111.75
  5032.7  111.75  5035.2  116.75  5068.6   117.5  5098.6  116.91  5118.6  117.47
  5128.6  117.04  5258.6  117.36  5318.6  116.91  5368.6  117.31  5388.6  117.97
  5398.6  119.58  5428.6  126.72  5448.6  132.06  5458.6  133.93  5488.6   137.4
  5568.6  141.84  5598.6  142.58  5628.6  144.95  5668.6     146  5698.6  148.47
  5718.6  148.21  5778.6  149.46  5908.6  153.63  5938.6  154.01    6520  154.12
#Mann= 3 ,-1 , 0
  3679.1    .145       0  4964.8     .05       0  5035.2    .145       0
Bank Sta=4964.8,5035.2
XS Rating Curve= 0 ,0
Exp/Cntr=0.3,0.1

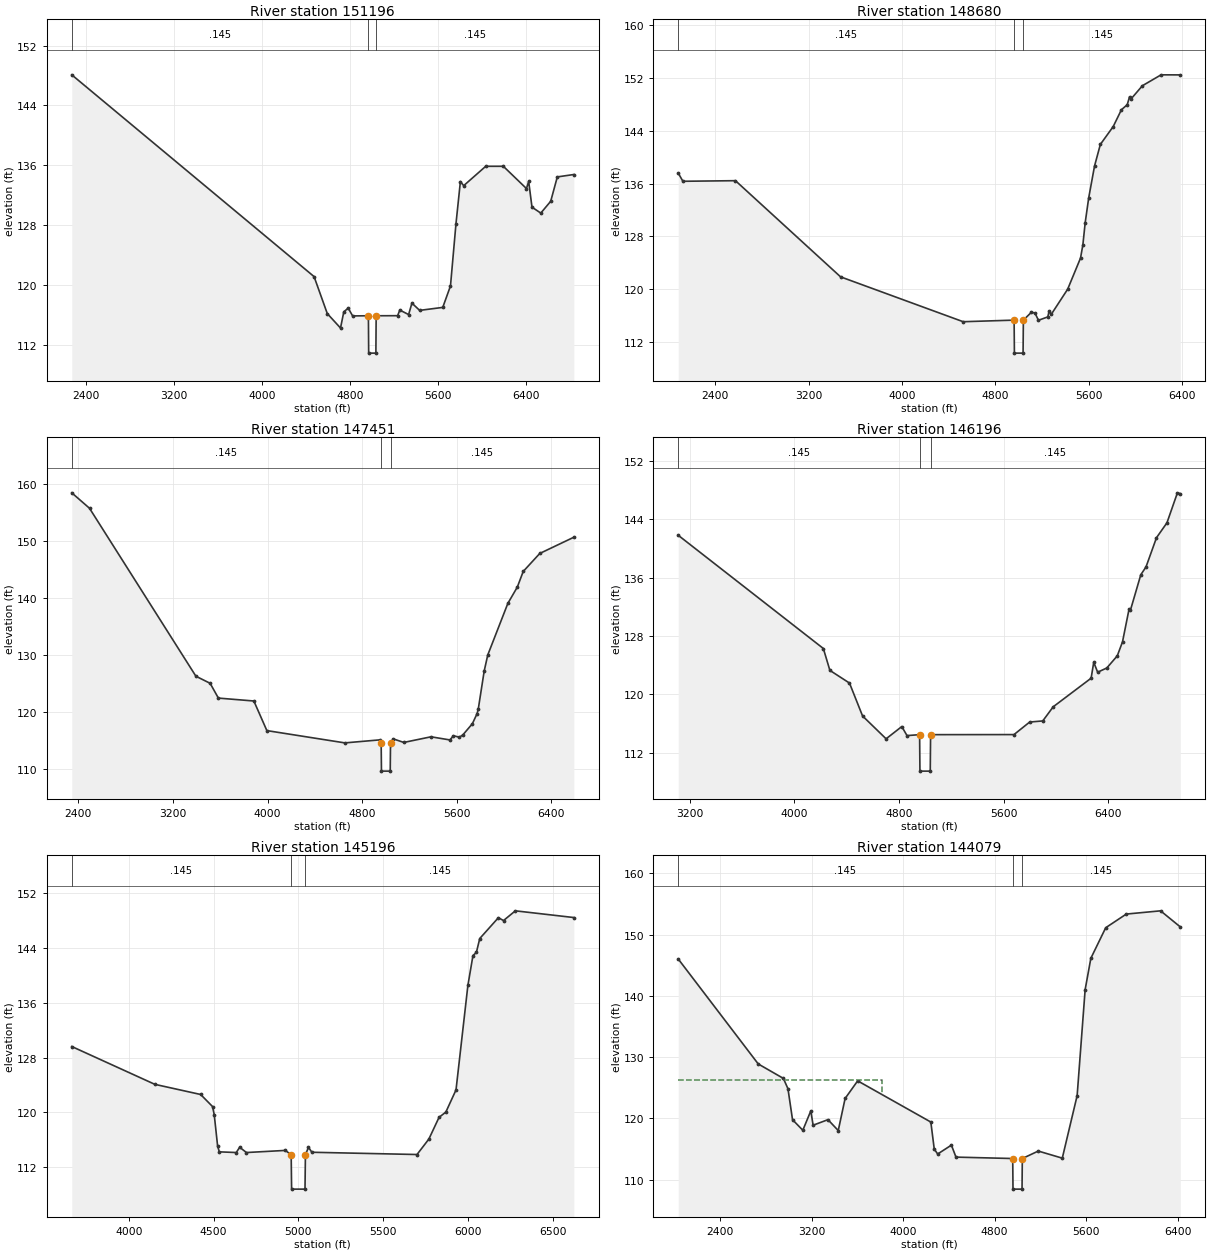
Type RM Length L Ch R = 1 ,151196  ,2516,2516,2516
BEGIN DESCRIPTION:
Four Hole Swamp 169.0
END DESCRIPTION:
XS GIS Cut Line= 3
       2102841.4       601521.68      2100913.96       599590.43
      2099395.33       598569.15
#Sta/Elev= 30
  2271.5   148.1  4471.5   121.1  4591.5  116.15  4711.5  114.22  4741.5  116.39
  4781.5  116.88  4821.5  115.84  4964.8  115.86  4967.3  110.86  5032.7  110.86
  5035.2  115.86    5230  115.87    5250  116.62    5330  116.02    5360  117.55
    5430  116.58    5640  116.98    5710  119.85    5760  128.19    5800  133.82
    5830  133.27    6030  135.86    6190  135.86    6400  132.88    6420  133.84
    6450  130.39    6530   129.6    6620  131.18    6680  134.44  6830.1  134.76
#Mann= 3 ,-1 , 0
  2271.5    .145       0  4964.8     .05       0  5035.2    .145       0
Bank Sta=4964.8,5035.2
XS Rating Curve= 0 ,0
Exp/Cntr=0.3,0.1

Type RM Length L Ch R = 1 ,148680  ,1229,1229,1229
BEGIN DESCRIPTION:
Four Hole Swamp 166.0
END DESCRIPTION:
XS GIS Cut Line= 3
      2103786.32        599628.2      2101725.17       597567.04
      2100746.12         596588.
#Sta/Elev= 30
  2084.1   137.6  2124.1  136.36  2574.1  136.45  3474.1  121.88  4524.1  115.08
  4960.4  115.32  4962.9  110.32  5037.1  110.32  5039.6  115.32    5109  116.52
    5139  116.39    5169   115.3    5249  115.81    5259  116.63    5279  116.21
    5419  120.01    5529  124.72    5549   126.7    5569  130.08    5599  133.83
    5649  138.67    5699  141.95    5809  144.65    5879  147.19    5929  147.96
    5949  149.17    5959  148.78    6059  150.84    6219  152.49  6383.6  152.48
#Mann= 3 ,-1 , 0
  2084.1    .145       0  4960.4     .05       0  5039.6    .145       0
Bank Sta=4960.4,5039.6
XS Rating Curve= 0 ,0
Exp/Cntr=0.3,0.1

Type RM Length L Ch R = 1 ,147451  ,1255,1255,1255
BEGIN DESCRIPTION:
Four Hole Swamp 165.0
END DESCRIPTION:
XS GIS Cut Line= 3
      2104997.94       598507.87       2102745.4        597096.5
      2101399.62       596253.29
#Sta/Elev= 30
  2343.7  158.45  2493.7  155.74  3393.7  126.23  3513.7  124.99  3583.7  122.39
  3883.7  121.88  3993.7  116.68  4653.7  114.52  4953.7  115.06  4960.4  114.56
  4962.9  109.56  5037.1  109.56  5039.6  114.56  5061.9  115.23  5151.9   114.6
  5381.9  115.59  5541.9  115.04  5571.9  115.78  5621.9  115.51  5651.9  115.94
  5731.9  117.89  5771.9  119.67  5781.9  120.49  5831.9  127.16  5861.9  129.96
  6031.9  139.03  6111.9  141.89  6161.9  144.64  6301.9   147.8    6590  150.65
#Mann= 3 ,-1 , 0
  2343.7    .145       0  4960.4     .05       0  5039.6    .145       0
Bank Sta=4960.4,5039.6
XS Rating Curve= 0 ,0
Exp/Cntr=0.3,0.1

Type RM Length L Ch R = 1 ,146196  ,1000,1000,1000
BEGIN DESCRIPTION:
Four Hole Swamp 164.0
END DESCRIPTION:
XS GIS Cut Line= 3
      2105322.36        597311.8      2103651.82       596431.46
      2101935.35        595501.5
#Sta/Elev= 30
  3111.7   141.8  4221.7  126.28  4271.7  123.28  4421.7  121.54  4521.7  117.03
  4701.7   113.9  4821.7  115.58  4861.7  114.34    4958  114.47  4960.5  109.47
  5039.5  109.47    5042  114.47    5680  114.48    5800   116.2    5900  116.35
    5980  118.29    6270  122.21    6290  124.39    6320  123.03    6390  123.61
    6470  125.27    6510  127.19    6560  131.67    6570  131.49    6650  136.39
    6690  137.47    6770  141.47    6850  143.51    6930  147.62  6952.2  147.51
#Mann= 3 ,-1 , 0
  3111.7    .145       0    4958     .05       0    5042    .145       0
Bank Sta=4958,5042
XS Rating Curve= 0 ,0
Exp/Cntr=0.3,0.1

Type RM Length L Ch R = 1 ,145196  ,1117,1117,1117
BEGIN DESCRIPTION:
Four Hole Swamp 163.0
END DESCRIPTION:
XS GIS Cut Line= 3
      2105109.42       596146.07      2103898.18       595582.81
      2102443.62       594858.78
#Sta/Elev= 30
  3664.2  129.62  4154.2   124.1  4424.2  122.62  4494.2  120.86  4504.2  119.69
  4524.2   115.1  4534.2  114.25  4634.2  114.15  4654.2  114.92  4694.2  114.15
  4924.2  114.46    4958  113.81  4960.5  108.81  5039.5  108.81    5042  113.81
    5060  114.92    5080  114.19    5700  113.86    5770  116.12    5830  119.29
    5870  120.05    5930  123.29    6000  138.54    6030   142.9    6050  143.34
    6070  145.38    6180  148.42    6210     148    6280  149.42  6624.8  148.44
#Mann= 3 ,-1 , 0
  3664.2    .145       0    4958     .05       0    5042    .145       0
Bank Sta=4958,5042
XS Rating Curve= 0 ,0
Exp/Cntr=0.3,0.1

Type RM Length L Ch R = 1 ,144079  ,1591,1591,1591
BEGIN DESCRIPTION:
Four Hole Swamp 162.0
END DESCRIPTION:
XS GIS Cut Line= 3
      2106711.03       596125.82      2104059.63       594787.39
      2102788.18       594149.19
#Sta/Elev= 30
  2031.6  146.03  2731.6  128.88  2951.6  126.52  2991.6  124.83  3031.6  119.77
  3121.6  118.05  3191.6  121.22  3211.6  118.87  3341.6  119.78  3431.6     118
  3491.6  123.24  3601.6  126.12  4241.6  119.39  4271.6  114.96  4301.6  114.17
  4421.6  115.62  4461.6  113.66    4958  113.43  4960.5  108.43  5039.5  108.43
    5042  113.43  5181.7  114.65  5391.7  113.49  5521.7  123.71  5591.7  141.03
  5641.7  146.15  5771.7  151.14  5951.7  153.37  6251.7   153.9  6424.3  151.27
#Mann= 3 ,-1 , 0
  2031.6    .145       0    4958     .05       0    5042    .145       0
#XS Ineff= 2 , 0
       0  3818.7  126.24               0
Permanent Ineff=
       F       F
Bank Sta=4958,5042
XS Rating Curve= 0 ,0
Exp/Cntr=0.3,0.1