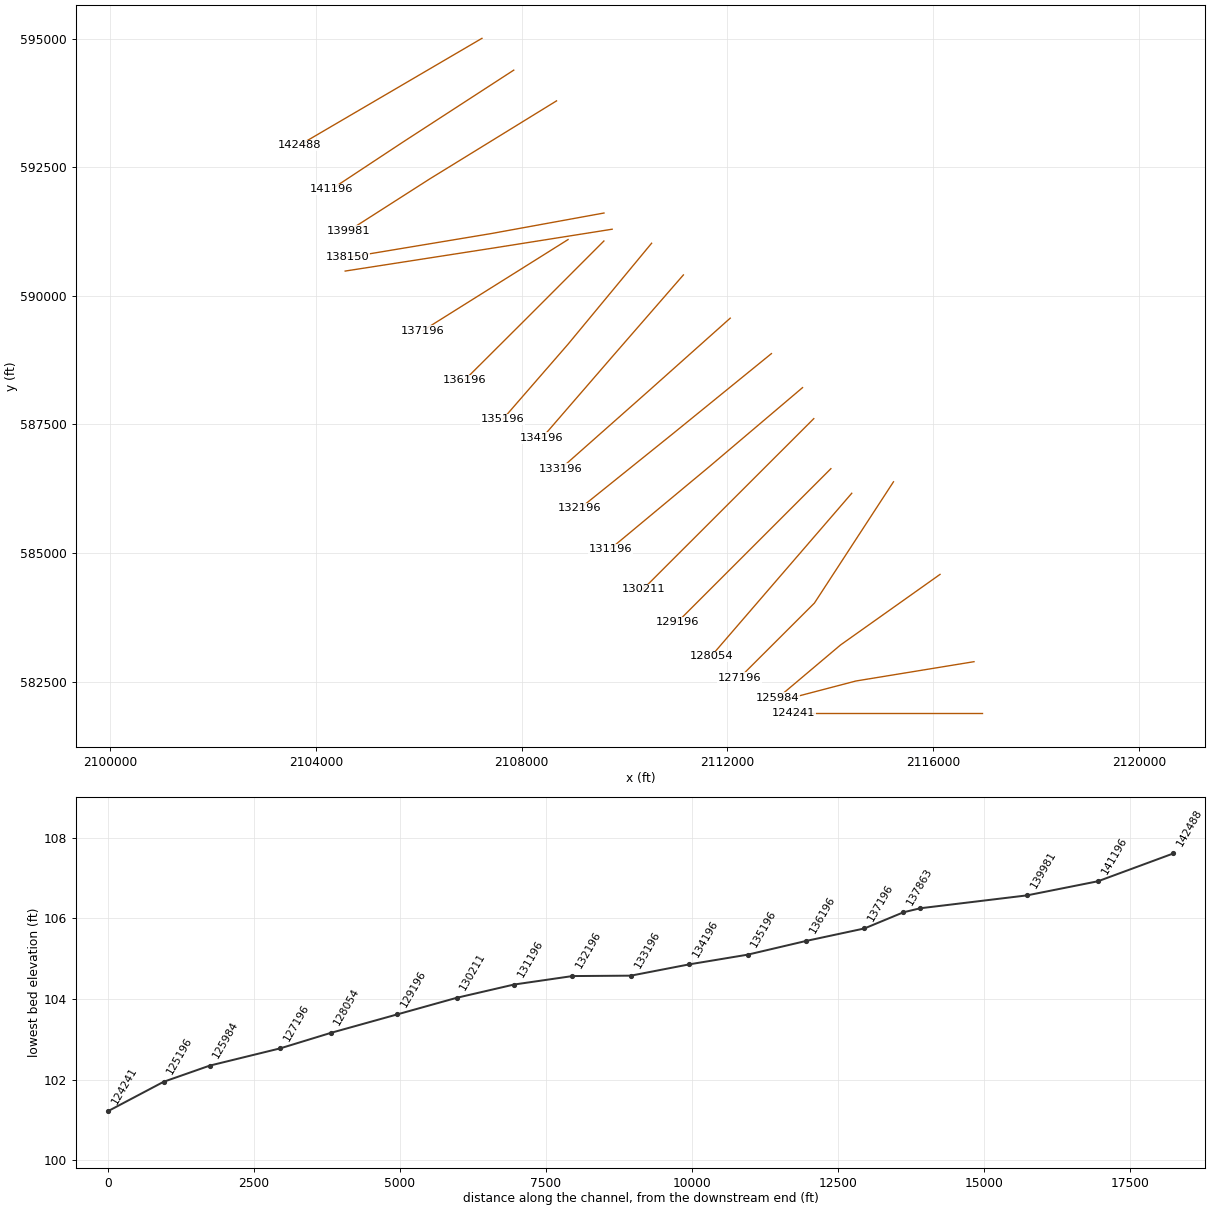
HEC-RAS study SCDOTFEMA.prj: SCDOTFEMAFourHoleSwampLimitedDetailStudy

--- SCDOTFEMA.g02 (geometry) --- (continued)

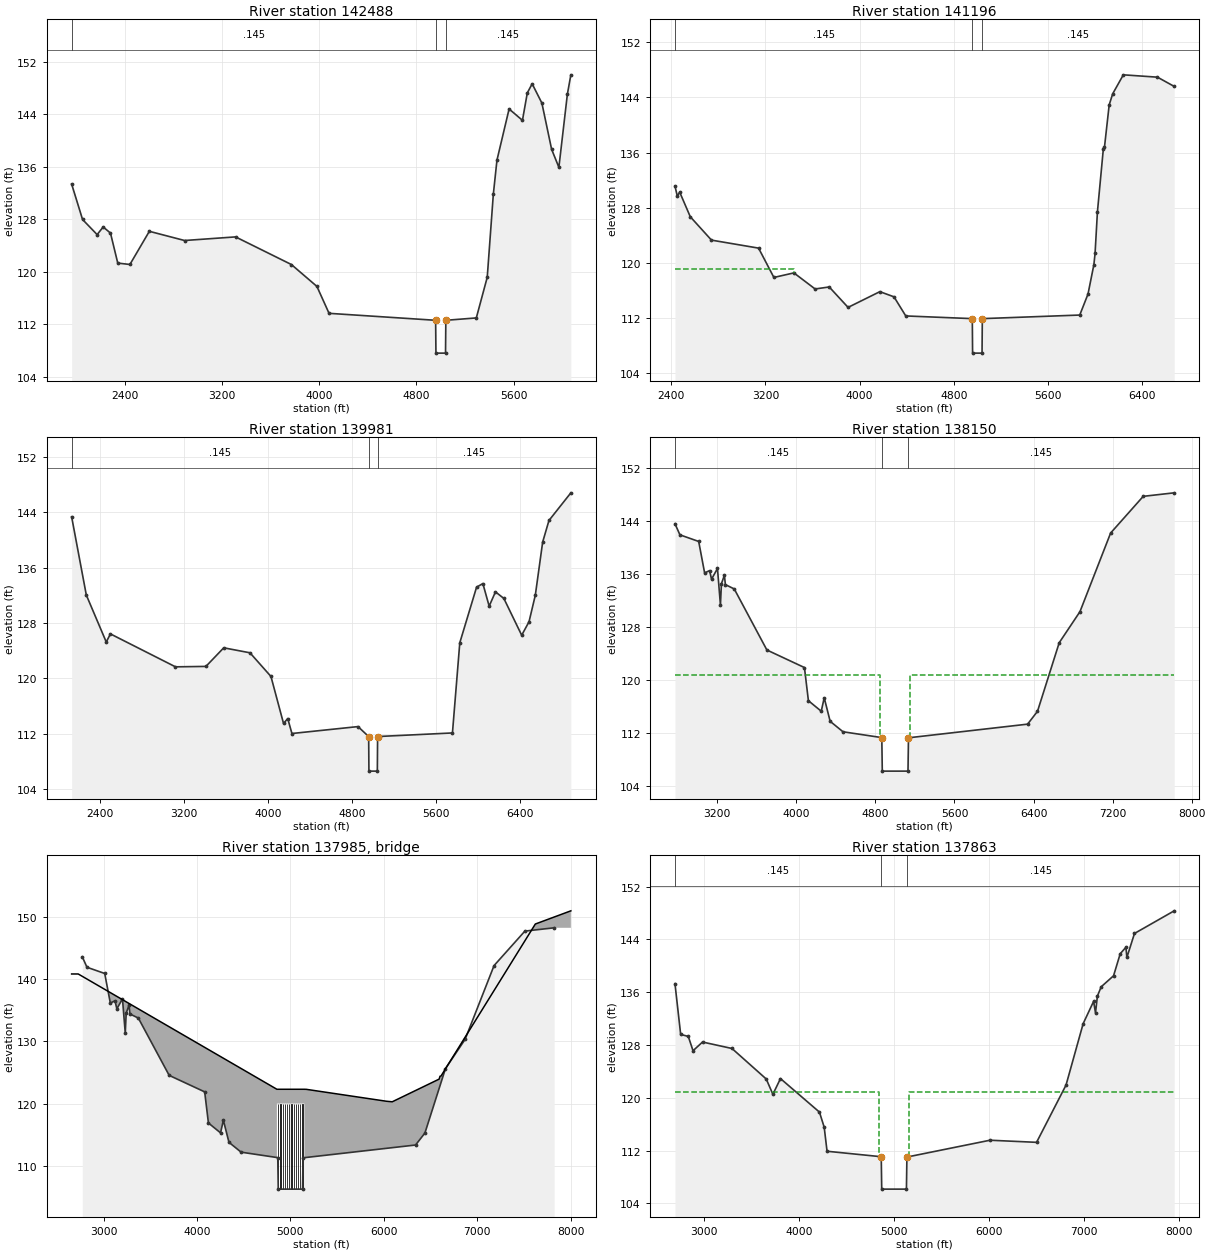
Type RM Length L Ch R = 1 ,142488  ,1292,1292,1292
BEGIN DESCRIPTION:
Four Hole Swamp 160.0
END DESCRIPTION:
XS GIS Cut Line= 3
      2107228.01       595010.82      2104593.77       593467.91
      2103680.26       592932.85
#Sta/Elev= 30
  1960.2  133.36  2050.2  127.96  2170.2  125.66  2220.2  126.82  2280.2  125.89
  2340.2  121.32  2440.2  121.11  2600.2  126.16  2890.2  124.76  3310.2  125.31
  3770.2   121.1  3980.2  117.77  4080.2  113.67    4958  112.61  4960.5  107.61
  5039.5  107.61    5042  112.61    5293  112.97    5383  119.16    5433  131.77
    5463  136.99    5563  144.79    5673  143.06    5713  147.24    5753  148.62
    5833  145.69    5913  138.66    5973   135.9    6043  147.04  6071.7  149.99
#Mann= 3 ,-1 , 0
  1960.2    .145       0    4958     .05       0    5042    .145       0
Bank Sta=4958,5042
XS Rating Curve= 0 ,0
Exp/Cntr=0.3,0.1

Type RM Length L Ch R = 1 ,141196  ,1215,1215,1215
BEGIN DESCRIPTION:
Four Hole Swamp 159.0
END DESCRIPTION:
XS GIS Cut Line= 3
      2107846.28       594392.47      2105693.36       592993.36
      2104298.52       592071.22
#Sta/Elev= 30
  2432.4  131.13  2452.4  129.68  2472.4  130.26  2562.4  126.69  2742.4   123.3
  3142.4  122.14  3272.4  117.89  3442.4  118.55  3622.4  116.22  3742.4  116.51
  3902.4  113.55  4172.4  115.83  4292.4  115.08  4392.4  112.31  4957.4  111.92
  4959.9  106.92  5040.1  106.92  5042.6  111.92    5870  112.44    5940  115.48
    5990  119.75    6000  121.37    6020  127.39    6070  136.47    6080  136.79
    6120  142.91    6150  144.52    6240  147.26    6530  146.92  6672.1  145.58
#Mann= 3 ,-1 , 0
  2432.4    .145       0  4957.4     .05       0  5042.6    .145       0
#XS Ineff= 2 , 0
       0  3439.4  119.09               0
Permanent Ineff=
       F       F
Bank Sta=4957.4,5042.6
XS Rating Curve= 0 ,0
Exp/Cntr=0.3,0.1

Type RM Length L Ch R = 1 ,139981  ,1831,1831,1831
BEGIN DESCRIPTION:
Four Hole Swamp 158.0
END DESCRIPTION:
XS GIS Cut Line= 3
      2108677.52       593794.44       2106216.8       592278.58
      2104643.18       591270.45
#Sta/Elev= 30
  2125.9  143.35  2265.9  132.03  2455.9  125.24  2495.9  126.41  3115.9  121.65
  3405.9  121.71  3575.9   124.4  3825.9  123.68  4025.9  120.26  4145.9  113.46
  4185.9  114.17  4225.9  112.01  4855.9  113.01  4957.4  111.57  4959.9  106.57
  5040.1  106.57  5042.6  111.57  5756.1  112.09  5826.1  125.13  5986.1  133.17
  6046.1  133.69  6106.1  130.42  6166.1  132.49  6246.1  131.54  6416.1  126.22
  6486.1  128.17  6546.1  132.01  6616.1  139.69  6676.1  142.81  6884.9  146.81
#Mann= 3 ,-1 , 0
  2125.9    .145       0  4957.4     .05       0  5042.6    .145       0
Bank Sta=4957.4,5042.6
XS Rating Curve= 0 ,0
Exp/Cntr=0.5,0.3

Type RM Length L Ch R = 1 ,138150  ,287,287,287
BEGIN DESCRIPTION:
Five Chop Road - US
END DESCRIPTION:
XS GIS Cut Line= 3
       2109599.6       591613.02      2107408.05       591213.21
      2104623.03       590749.38
#Sta/Elev= 30
  2772.4  143.59  2822.4  141.91  3012.4  140.91  3072.4  136.16  3122.4  136.51
  3142.4  135.22  3202.4  136.83  3232.4  131.32  3242.4  134.54  3272.4   135.8
  3282.4   134.4  3372.4  133.74  3702.4  124.53  4082.4  121.88  4122.4  116.88
  4252.4  115.29  4282.4  117.32  4342.4  113.77  4472.4  112.19    4865  111.31
    4870  106.25    5130  106.25    5135  111.28  6340.1  113.34  6440.1  115.27
  6660.1  125.63  6870.1  130.32  7180.1  142.18  7510.1  147.72  7823.5  148.25
#Mann= 3 ,-1 , 0
  2772.4    .145       0    4865     .05       0    5135    .145       0
#XS Ineff= 2 , 0
       0  4848.6  120.83  5151.4       0  120.83
Permanent Ineff=
       F       F
Bank Sta=4865,5135
XS Rating Curve= 0 ,0
Exp/Cntr=0.5,0.3

Type RM Length L Ch R = 3 ,137985  ,,,
BEGIN DESCRIPTION:
Five Chop Road - TOR
Structure ID: LDS_FHS_06A
Approximate Survey Structure
END DESCRIPTION:
Bridge Culvert--1,0,-1,-1, 0
Deck Dist Width WeirC Skew NumUp NumDn MinLoCord MaxHiCord MaxSubmerge Is_Ogee
97.33,105.17,3,0, 14, 14, , , 0.95, 0, 1,1,,
  2658.2  2728.8  4855.5  4855.5  5149.5  5149.5  5170.2  6030.2  6090.2  6591.8
  6601.8  6611.8  7621.8  8002.2
  140.83  140.83   122.3   122.3   122.3   122.3  122.29  120.37  120.29  123.93
   124.4  124.42  148.86  150.98
   88.33   88.33   88.33     120     120   88.33   88.33   88.33   88.33   88.33
   88.33   88.33   88.33   88.33
  2658.2  2728.8  4855.5  4855.5  5145.5  5145.5  5170.2  6030.2  6090.2  6591.8
  6601.8  6611.8  7621.8  8002.2
  140.83  140.83  120.73  120.73  120.73  120.73  120.53  120.37  120.29  123.93
   124.4  124.42  148.86  150.98
   88.33   88.33   88.33  119.43  119.43   88.33   88.33   88.33   88.33   88.33
   88.33   88.33   88.33   88.33
Pier Skew, UpSta & Num, DnSta & Num=  ,4870.3, 2 ,4870.3, 2 , 0 , 0 , 0 ,0,0
     1.5     1.5
  108.33     120
     1.5     1.5
  108.08  119.43
Pier Skew, UpSta & Num, DnSta & Num=  ,4893.9, 2 ,4893.9, 2 , 0 , 0 , 0 ,0,0
     1.5     1.5
  108.33     120
     1.5     1.5
  108.08  119.43
Pier Skew, UpSta & Num, DnSta & Num=  ,4917.5, 2 ,4917.5, 2 , 0 , 0 , 0 ,0,0
     1.5     1.5
  108.33     120
     1.5     1.5
  108.08  119.43
Pier Skew, UpSta & Num, DnSta & Num=  ,4941, 2 ,4941, 2 , 0 , 0 , 0 ,0,0
     1.5     1.5
  108.33     120
     1.5     1.5
  108.08  119.43
Pier Skew, UpSta & Num, DnSta & Num=  ,4964.6, 2 ,4964.6, 2 , 0 , 0 , 0 ,0,0
     1.5     1.5
  108.33     120
     1.5     1.5
  108.08  119.43
Pier Skew, UpSta & Num, DnSta & Num=  ,4988.2, 2 ,4988.2, 2 , 0 , 0 , 0 ,0,0
     1.5     1.5
  108.33     120
     1.5     1.5
  108.08  119.43
Pier Skew, UpSta & Num, DnSta & Num=  ,5011.8, 2 ,5011.8, 2 , 0 , 0 , 0 ,0,0
     1.5     1.5
  108.33     120
     1.5     1.5
  108.08  119.43
Pier Skew, UpSta & Num, DnSta & Num=  ,5035.4, 2 ,5035.4, 2 , 0 , 0 , 0 ,0,0
     1.5     1.5
  108.33     120
     1.5     1.5
  108.08  119.43
Pier Skew, UpSta & Num, DnSta & Num=  ,5059, 2 ,5059, 2 , 0 , 0 , 0 ,0,0
     1.5     1.5
  108.33     120
     1.5     1.5
  108.08  119.43
Pier Skew, UpSta & Num, DnSta & Num=  ,5082.5, 2 ,5082.5, 2 , 0 , 0 , 0 ,0,0
     1.5     1.5
  108.33     120
     1.5     1.5
  108.08  119.43
Pier Skew, UpSta & Num, DnSta & Num=  ,5106.1, 2 ,5106.1, 2 , 0 , 0 , 0 ,0,0
     1.5     1.5
  108.33     120
     1.5     1.5
  108.08  119.43
Pier Skew, UpSta & Num, DnSta & Num=  ,5129.7, 2 ,5129.7, 2 , 0 , 0 , 0 ,0,0
     1.5     1.5
  108.33     120
     1.5     1.5
  108.08  119.43
Abutment Skew #Up #Dn= , 2 , 2
  4855.5    4867
     120  108.33
  4855.5    4867
  119.43  108.08
Abutment Skew #Up #Dn= , 2 , 2
    5138  5149.5
  108.33     120
    5134  5145.5
  108.08  119.43
BR Coef= 1 , 1 , 0 ,1.25, 0 ,,,0.8,0,2,0,
WSPro=,,,, 1 ,,,, 0 ,,,, 0 ,,,,-1 ,-1 ,-1 , 0 , 0 , 0 , 0 , 0
BC Design=,, 0 ,, 0 ,,,,,,
BC HTab HWMax=148.63
BC Use User HTab Curves=0
BC User HTab FreeFlow(D)= 0

Type RM Length L Ch R = 1 ,137863  ,667,667,667
BEGIN DESCRIPTION:
Five Chop Road - DS
END DESCRIPTION:
XS GIS Cut Line= 3
      2109758.79       591297.99      2107482.94       590936.97
      2104569.97       590483.92
#Sta/Elev= 30
  2694.9  137.28  2754.9  129.59  2834.9  129.29  2884.9  127.12  2984.9  128.44
  3294.9  127.46  3654.9  122.84  3724.9  120.52  3804.9   122.9  4214.9  117.82
  4264.9  115.53  4294.9  111.89    4865  111.06    4870  106.15    5130  106.15
    5135  111.01  6009.2  113.56  6499.2  113.24  6809.2  121.92  6989.2  131.22
  7099.2   134.6  7119.2  132.86  7139.2  135.41  7179.2  136.81  7309.2  138.48
  7379.2  141.82  7439.2   142.8  7449.2  141.25  7529.2  144.89  7947.2  148.32
#Mann= 3 ,-1 , 0
  2694.9    .145       0    4865     .05       0    5135    .145       0
#XS Ineff= 2 , 0
       0  4844.3  120.84  5155.7       0  120.84
Permanent Ineff=
       F       F
Bank Sta=4865,5135
XS Rating Curve= 0 ,0
Exp/Cntr=0.5,0.3

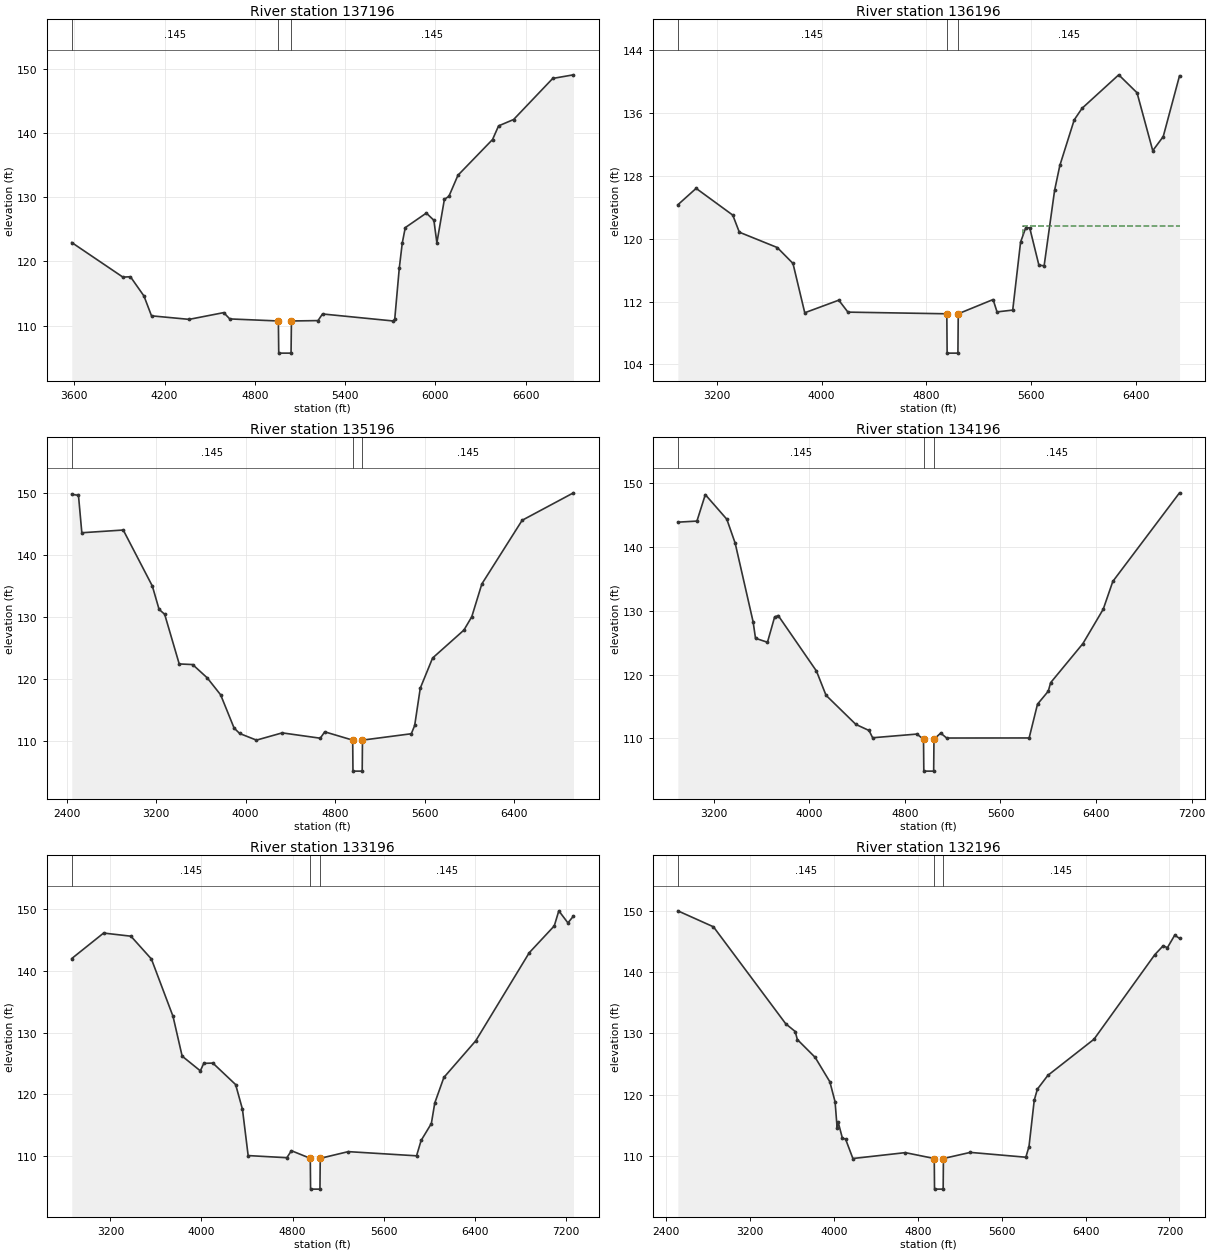
Type RM Length L Ch R = 1 ,137196  ,1000,1000,1000
BEGIN DESCRIPTION:
Four Hole Swamp 155.0
END DESCRIPTION:
XS GIS Cut Line= 3
      2108901.53       591096.56      2107702.09       590343.02
      2106077.53       589324.03
#Sta/Elev= 30
  3583.5  122.95  3923.5  117.57  3973.5  117.63  4063.5  114.63  4113.5  111.55
  4363.5     111  4593.5  112.05  4633.5  111.07  4956.6  110.75  4959.1  105.75
  5040.9  105.75  5043.4  110.75    5220  110.81    5250  111.84    5720  110.75
    5730  111.03    5760  118.93    5780  122.87    5800  125.27    5940  127.53
    5990  126.41    6010  122.91    6060  129.67    6090  130.14    6150  133.41
    6380  138.97    6420  141.09    6520  142.08    6780  148.47  6917.7  149.03
#Mann= 3 ,-1 , 0
  3583.5    .145       0  4956.6     .05       0  5043.4    .145       0
Bank Sta=4956.6,5043.4
XS Rating Curve= 0 ,0
Exp/Cntr=0.3,0.1

Type RM Length L Ch R = 1 ,136196  ,1000,1000,1000
BEGIN DESCRIPTION:
Four Hole Swamp 154.0
END DESCRIPTION:
XS GIS Cut Line= 3
      2109597.99       591068.59      2108115.15        589582.7
      2106887.08       588357.68
#Sta/Elev= 30
  2900.8  124.29  3040.8  126.38  3320.8  122.98  3370.8  120.81  3660.8  118.86
  3780.8  116.84  3870.8  110.57  4130.8  112.17  4200.8  110.65  4956.3  110.44
  4958.8  105.44  5041.2  105.44  5043.7  110.44    5310  112.25    5340  110.68
    5460  110.91    5520  119.55    5560   121.4    5590  121.35    5660  116.62
    5700  116.54    5780  126.13    5820  129.29    5930  135.09    5990  136.56
    6270  140.81    6410  138.53    6530  131.17    6610  132.96  6734.6  140.69
#Mann= 3 ,-1 , 0
  2900.8    .145       0  4956.3     .05       0  5043.7    .145       0
#XS Ineff= 2 , 0
       0                  5539.8       0  121.56
Permanent Ineff=
       F       F
Bank Sta=4956.3,5043.7
XS Rating Curve= 0 ,0
Exp/Cntr=0.3,0.1

Type RM Length L Ch R = 1 ,135196  ,1000,1000,1000
BEGIN DESCRIPTION:
Four Hole Swamp 153.0
END DESCRIPTION:
XS GIS Cut Line= 3
      2110524.99       591024.99      2108897.91       589057.13
      2107633.43       587601.04
#Sta/Elev= 30
  2446.6  149.74  2506.6  149.59  2536.6  143.55  2906.6  143.99  3166.6  134.95
  3226.6   131.2  3276.6   130.4  3406.6  122.39  3526.6  122.29  3656.6  120.15
  3776.6  117.41  3896.6  112.06  3946.6  111.17  4096.6   110.1  4326.6  111.27
  4666.6  110.41  4706.6  111.44  4956.3   110.1  4958.8   105.1  5041.2   105.1
  5043.7   110.1    5480  111.13    5510  112.46    5560  118.48    5670  123.34
    5950  127.85    6020     130    6110  135.29    6470  145.56  6928.5  149.99
#Mann= 3 ,-1 , 0
  2446.6    .145       0  4956.3     .05       0  5043.7    .145       0
Bank Sta=4956.3,5043.7
XS Rating Curve= 0 ,0
Exp/Cntr=0.3,0.1

Type RM Length L Ch R = 1 ,134196  ,1000,1000,1000
BEGIN DESCRIPTION:
Four Hole Swamp 152.0
END DESCRIPTION:
XS GIS Cut Line= 3
      2111142.62       590408.45       2109765.6       588823.74
      2108393.71       587236.18
#Sta/Elev= 30
  2900.6  143.89  3060.6  144.06  3130.6  148.21  3310.6  144.35  3380.6  140.59
  3530.6  128.27  3550.6  125.69  3650.6  125.06  3710.6  129.03  3740.6  129.25
  4060.6  120.55  4140.6  116.75  4390.6  112.18  4500.6  111.23  4530.6  110.09
  4900.6  110.67  4956.3  109.86  4958.8  104.86  5041.2  104.86  5043.7  109.86
    5100  110.82    5150  110.05    5840  110.06    5910  115.36    6000  117.39
    6020  118.73    6290  124.86    6460  130.25    6540   134.6  7098.2  148.49
#Mann= 3 ,-1 , 0
  2900.6    .145       0  4956.3     .05       0  5043.7    .145       0
Bank Sta=4956.3,5043.7
XS Rating Curve= 0 ,0
Exp/Cntr=0.3,0.1

Type RM Length L Ch R = 1 ,133196  ,1000,1000,1000
BEGIN DESCRIPTION:
Four Hole Swamp 151.0
END DESCRIPTION:
XS GIS Cut Line= 3
      2112052.91        589567.5      2110456.79       588142.46
      2108758.59       586638.09
#Sta/Elev= 30
  2860.3  142.03  3140.3  146.17  3380.3  145.66  3560.3  141.95  3750.3  132.63
  3830.3  126.18  3990.3  123.79  4020.3  125.01  4100.3  125.05  4300.3  121.56
  4360.3  117.55  4410.3  110.03  4750.3  109.68  4790.3  110.82  4956.3  109.58
  4958.8  104.58  5041.2  104.58  5043.7  109.58    5290  110.67    5890  109.99
    5930  112.48    6020  115.23    6050  118.57    6130  122.72    6410  128.67
    6880  142.97    7100  147.33    7140  149.78    7220  147.82  7268.7  148.93
#Mann= 3 ,-1 , 0
  2860.3    .145       0  4956.3     .05       0  5043.7    .145       0
Bank Sta=4956.3,5043.7
XS Rating Curve= 0 ,0
Exp/Cntr=0.3,0.1

Type RM Length L Ch R = 1 ,132196  ,1000,1000,1000
BEGIN DESCRIPTION:
Four Hole Swamp 150.0
END DESCRIPTION:
XS GIS Cut Line= 3
      2112853.75       588878.27      2110922.18       587307.09
      2109133.63       585867.71
#Sta/Elev= 30
  2510.1  150.02  2850.1  147.41  3540.1  131.56  3630.1  130.31  3650.1     129
  3820.1  126.09  3960.1  122.11  4010.1  118.84  4030.1  114.51  4040.1  115.48
  4080.1  112.88  4110.1  112.75  4180.1  109.57  4680.1  110.53  4956.3  109.57
  4958.8  104.57  5041.2  104.57  5043.7  109.57    5300  110.57    5830  109.78
    5860  111.53    5910  119.09    5940   120.9    6040  123.15    6480  129.05
    7060  142.86    7140  144.32    7180     144    7250  146.04  7295.8  145.52
#Mann= 3 ,-1 , 0
  2510.1    .145       0  4956.3     .05       0  5043.7    .145       0
Bank Sta=4956.3,5043.7
XS Rating Curve= 0 ,0
Exp/Cntr=0.3,0.1

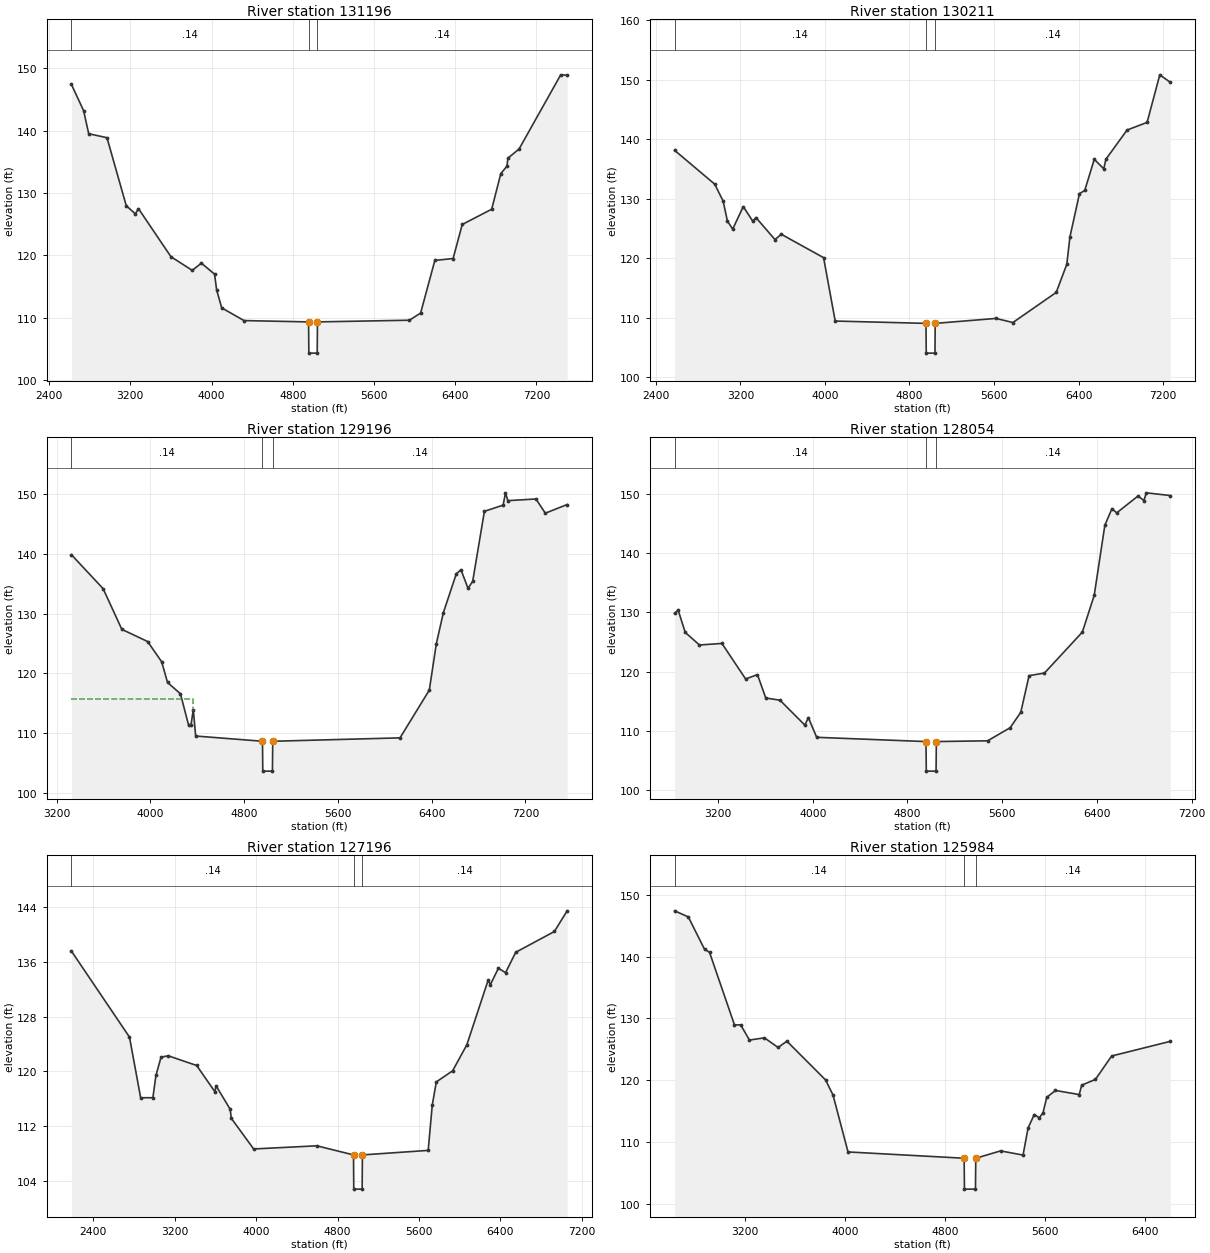
Type RM Length L Ch R = 1 ,131196  ,985,985,985
BEGIN DESCRIPTION:
Four Hole Swamp 149.0
END DESCRIPTION:
XS GIS Cut Line= 3
      2113458.24       588216.34      2111643.64       586676.64
      2109719.49       585075.02
#Sta/Elev= 30
  2620.2  147.38  2740.2  143.17  2790.2  139.49  2970.2  138.85  3160.2  127.96
  3250.2  126.65  3280.2   127.5  3600.2   119.8  3810.2  117.61  3900.2  118.77
  4030.2     117  4050.2  114.51  4100.2  111.61  4320.2  109.57  4956.3  109.36
  4958.8  104.36  5041.2  104.36  5043.7  109.36    5950  109.63    6060  110.78
    6200   119.2    6380  119.51    6470  124.96    6760   127.4    6850  133.11
    6910  134.28    6920  135.57    7030  137.05    7440  148.92  7503.5  148.86
#Mann= 3 ,-1 , 0
  2620.2     .14       0  4956.3     .05       0  5043.7     .14       0
Bank Sta=4956.3,5043.7
XS Rating Curve= 0 ,0
Exp/Cntr=0.3,0.1

Type RM Length L Ch R = 1 ,130211  ,1015,1015,1015
BEGIN DESCRIPTION:
Four Hole Swamp 148.0
END DESCRIPTION:
XS GIS Cut Line= 3
      2113676.79        587613.2      2111957.66       585894.07
      2110360.17       584296.59
#Sta/Elev= 30
  2577.4  138.11  2957.4  132.42  3037.4  129.56  3077.4  126.22  3127.4  124.87
  3227.4  128.65  3317.4   126.2  3347.4  126.81  3527.4  123.11  3587.4     124
  3987.4  120.07  4097.4  109.42  4956.3  109.03  4958.8  104.03  5041.2  104.03
  5043.7  109.03  5618.6  109.86  5778.6  109.17  6188.6  114.23  6288.6  118.95
  6318.6  123.57  6408.6  130.83  6458.6  131.36  6548.6   136.6  6638.6     135
  6658.6   136.6  6858.6  141.51  7048.6   142.8  7168.6  150.79  7267.8  149.54
#Mann= 3 ,-1 , 0
  2577.4     .14       0  4956.3     .05       0  5043.7     .14       0
Bank Sta=4956.3,5043.7
XS Rating Curve= 0 ,0
Exp/Cntr=0.3,0.1

Type RM Length L Ch R = 1 ,129196  ,1142,1142,1142
BEGIN DESCRIPTION:
Four Hole Swamp 147.0
END DESCRIPTION:
XS GIS Cut Line= 3
      2114009.31       586640.15      2112826.03       585456.03
      2111019.05       583647.86
#Sta/Elev= 30
    3326  139.85    3596  134.18    3756  127.36    3976  125.32    4096  121.93
    4146  118.47    4256  116.57    4326   111.3    4346  111.33    4366   113.9
    4386   109.5  4956.3  108.62  4958.8  103.62  5041.2  103.62  5043.7  108.62
    6130  109.19    6380  117.19    6440  124.97    6500  130.16    6610  136.65
    6650  137.34    6710  134.24    6750  135.38    6850  147.12    7010  148.16
    7030  150.22    7050  148.91    7290  149.19    7370  146.81  7556.3  148.26
#Mann= 3 ,-1 , 0
    3326     .14       0  4956.3     .05       0  5043.7     .14       0
#XS Ineff= 2 , 0
       0  4364.7  115.73               0
Permanent Ineff=
       F       F
Bank Sta=4956.3,5043.7
XS Rating Curve= 0 ,0
Exp/Cntr=0.3,0.1

Type RM Length L Ch R = 1 ,128054  ,858,858,858
BEGIN DESCRIPTION:
Four Hole Swamp 146.0
END DESCRIPTION:
XS GIS Cut Line= 3
      2114414.73       586161.67      2112995.63       584515.52
      2111681.97       582991.02
#Sta/Elev= 30
  2833.1  129.84  2863.1  130.41  2923.1  126.63  3043.1   124.5  3233.1  124.76
  3433.1  118.75  3533.1  119.49  3603.1  115.53  3723.1  115.16  3933.1  110.95
  3963.1  112.21  4033.1  108.88  4956.3  108.16  4958.8  103.16  5041.2  103.16
  5043.7  108.16  5476.5  108.29  5666.5   110.5  5756.5  113.11  5826.5  119.31
  5956.5  119.75  6276.5  126.68  6376.5  132.88  6466.5  144.76  6526.5  147.57
  6566.5  146.85  6746.5   149.7  6796.5  148.94  6816.5  150.24  7018.9  149.78
#Mann= 3 ,-1 , 0
  2833.1     .14       0  4956.3     .05       0  5043.7     .14       0
Bank Sta=4956.3,5043.7
XS Rating Curve= 0 ,0
Exp/Cntr=0.3,0.1

Type RM Length L Ch R = 1 ,127196  ,1212,1212,1212
BEGIN DESCRIPTION:
Four Hole Swamp 145.0
END DESCRIPTION:
XS GIS Cut Line= 3
      2115225.63       586384.65      2113689.45       584025.99
      2112235.42       582573.39
#Sta/Elev= 30
  2185.2  137.56  2755.2     125  2865.2  116.13  2985.2  116.14  3015.2  119.39
  3065.2  122.06  3135.2  122.27  3415.2  120.85  3595.2     117  3605.2   117.9
  3745.2  114.44  3755.2  113.14  3975.2  108.65  4595.2  109.11  4956.3  107.78
  4958.8  102.78  5041.2  102.78  5043.7  107.78    5690  108.44    5730  115.06
    5770  118.45    5930  120.07    6070  123.88    6280  133.36    6300  132.64
    6380  135.06    6450  134.41    6550  137.39    6930  140.43  7055.3  143.45
#Mann= 3 ,-1 , 0
  2185.2     .14       0  4956.3     .05       0  5043.7     .14       0
Bank Sta=4956.3,5043.7
XS Rating Curve= 0 ,0
Exp/Cntr=0.3,0.1

Type RM Length L Ch R = 1 ,125984  ,788,788,788
BEGIN DESCRIPTION:
Four Hole Swamp 144.0
END DESCRIPTION:
XS GIS Cut Line= 3
       2116130.5       584583.52      2114195.79       583209.94
      2112973.51        582177.8
#Sta/Elev= 30
  2632.8   147.4  2742.8  146.42  2872.8  141.18  2912.8  140.69  3112.8  128.94
  3162.8  128.93  3232.8  126.48  3352.8  126.84  3462.8  125.28  3532.8   126.3
  3842.8  120.03  3902.8  117.57  4022.8  108.37  4953.4  107.35  4955.9  102.35
  5044.1  102.35  5046.6  107.35  5245.5  108.54  5425.5  107.86  5465.5  112.23
  5515.5  114.43  5555.5  113.89  5585.5   114.7  5615.5  117.22  5685.5  118.32
  5875.5  117.66  5895.5  119.18  6005.5  120.11  6135.5   123.9  6605.3  126.27
#Mann= 3 ,-1 , 0
  2632.8     .14       0  4953.4     .05       0  5046.6     .14       0
Bank Sta=4953.4,5046.6
XS Rating Curve= 0 ,0
Exp/Cntr=0.3,0.1

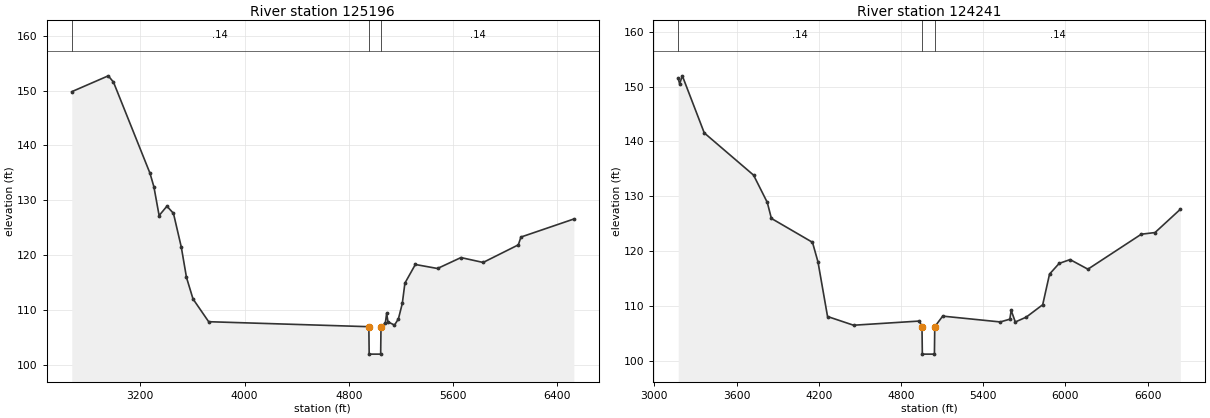
Type RM Length L Ch R = 1 ,125196  ,955,955,955
BEGIN DESCRIPTION:
Four Hole Swamp 143.0
END DESCRIPTION:
XS GIS Cut Line= 3
      2116790.73       582885.57      2114495.99       582509.84
      2113019.96       582123.31
#Sta/Elev= 30
  2674.7  149.79  2954.7  152.68  2994.7  151.53  3274.7  134.92  3304.7  132.45
  3344.7  127.21  3404.7  128.92  3454.7  127.61  3514.7  121.47  3554.7  115.92
  3604.7  112.01  3724.7  107.86  4953.4  106.95  4955.9  101.95  5044.1  101.95
  5046.6  106.95    5080  107.62    5090  109.41    5100  107.84    5150  107.24
    5180  108.36    5210  111.19    5230  114.89    5310  118.29    5480  117.56
    5660  119.55    5830  118.66    6100  121.87    6120  123.29  6525.8  126.58
#Mann= 3 ,-1 , 0
  2674.7     .14       0  4953.4     .05       0  5046.6     .14       0
Bank Sta=4953.4,5046.6
XS Rating Curve= 0 ,0
Exp/Cntr=0.3,0.1

Type RM Length L Ch R = 1 ,124241  ,1442,1442,1442
BEGIN DESCRIPTION:
Four Hole Swamp 142.0
END DESCRIPTION:
XS GIS Cut Line= 3
      2116944.76       581880.04      2115104.01       581880.04
      2113279.46       581880.04
#Sta/Elev= 30
  3173.9  151.49  3183.9  150.51  3203.9  151.97  3363.9  141.56  3723.9  133.86
  3823.9  128.89  3853.9  125.97  4153.9  121.61  4193.9  118.06  4263.9  108.08
  4453.9  106.49  4933.9  107.25  4953.4  106.22  4955.9  101.22  5044.1  101.22
  5046.6  106.22  5104.6  108.15  5524.6  107.09  5594.6  107.59  5604.6  109.19
  5634.6  107.08  5714.6  107.97  5834.6  110.23  5884.6  115.82  5954.6  117.76
  6034.6  118.46  6164.6  116.71  6554.6  123.09  6654.6  123.39  6839.2  127.63
#Mann= 3 ,-1 , 0
  3173.9     .14       0  4953.4     .05       0  5046.6     .14       0
Bank Sta=4953.4,5046.6
XS Rating Curve= 0 ,0
Exp/Cntr=0.3,0.1