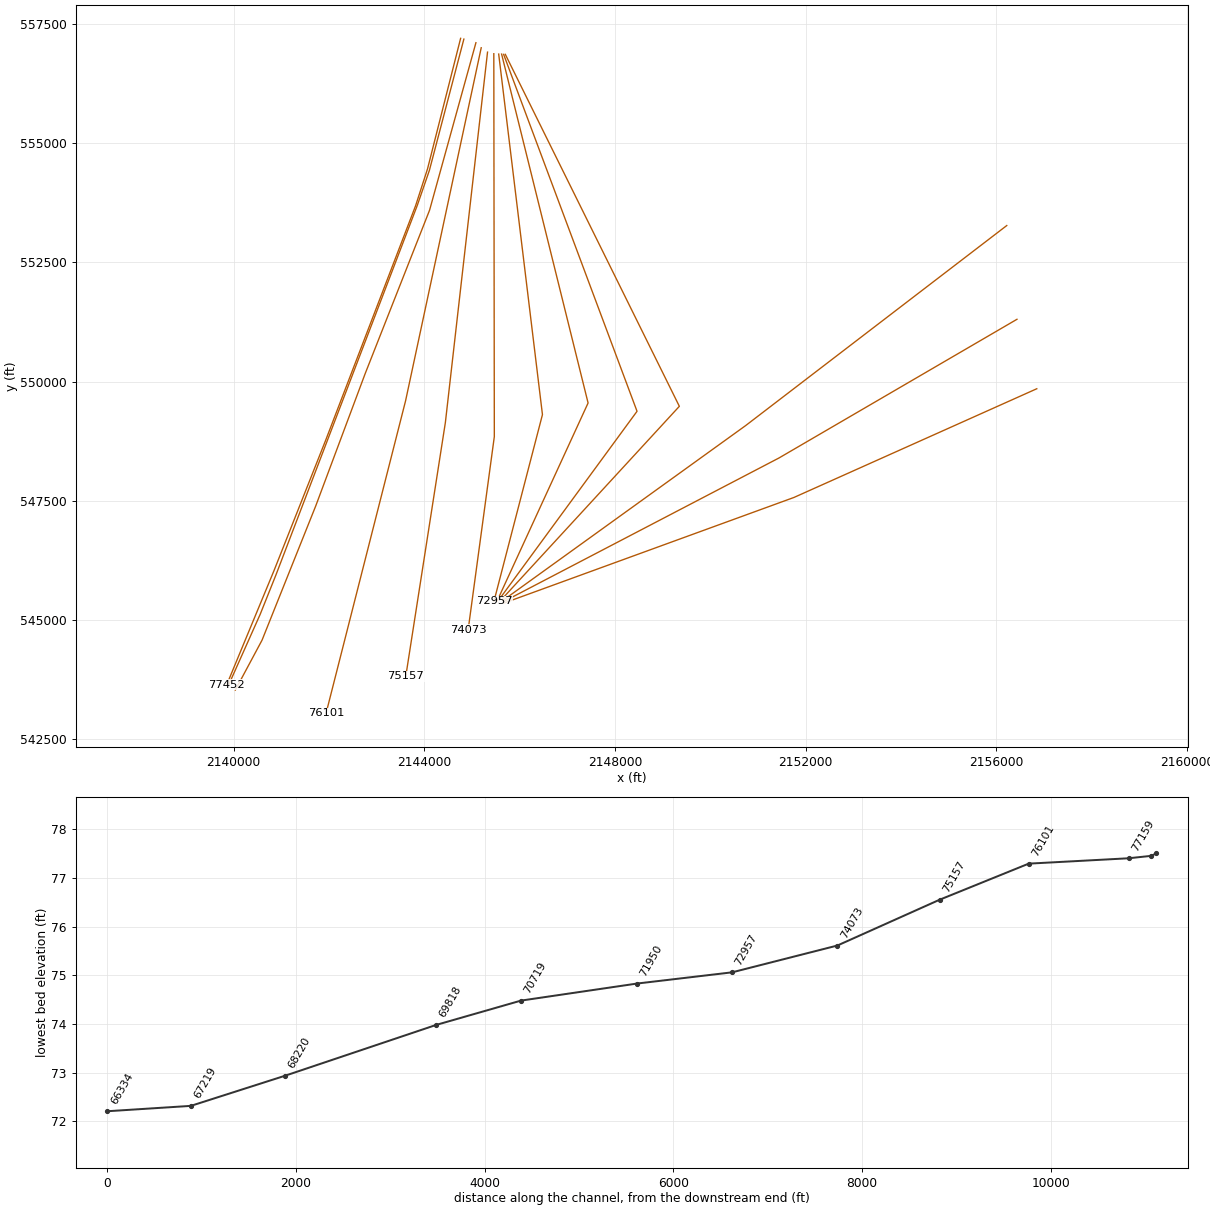
HEC-RAS study SCDOTFEMA.prj: SCDOTFEMAFourHoleSwampLimitedDetailStudy

--- SCDOTFEMA.g02 (geometry) --- (continued)

Type RM Length L Ch R = 3 ,77544   ,,,
BEGIN DESCRIPTION:
Highway I-95 South - TOR
Structure ID: LDS_FHS_02
Approximate Survey Structure
END DESCRIPTION:
Bridge Culvert--1,0,-1,-1, 0
Deck Dist Width WeirC Skew NumUp NumDn MinLoCord MaxHiCord MaxSubmerge Is_Ogee
123,38,3,0, 25, 25, , , 0.95, 0, 1,1,,
 -2208.2  1322.1  1342.1  1362.1  1382.1  1422.1  1442.1  1462.1  1482.1  1544.4
  4769.3  4882.5  4882.5  5117.5  5117.5  5238.4  7241.9  7279.2  7299.2  7319.2
  7479.2  7499.2  7519.2   11418 12227.5
   92.62   92.25   89.73   84.43   81.84   81.68   82.59   84.71   89.95    92.2
   92.69   92.69   92.69   92.69   92.69   92.69   92.81   91.78   85.81   82.75
   82.45   87.28   92.85   99.97  100.51
   60.59   60.59   60.59   60.59   60.59   60.59   60.59   60.59   60.59   60.59
   60.59   60.59   91.09   91.09   60.59   60.59   60.59   60.59   60.59   60.59
   60.59   60.59   60.59   60.59   60.59
 -2208.2  1322.1  1342.1  1362.1  1382.1  1422.1  1442.1  1462.1  1482.1  1544.4
  4769.3  4882.5  4882.5  5117.5  5117.5  5238.4  7241.9  7279.2  7299.2  7319.2
  7479.2  7499.2  7519.2   11418 12227.5
   92.62   92.25   89.73   84.43   81.84   81.68   82.59   84.71   89.95    92.2
   92.69   92.69   92.69   92.69   92.69   92.69   92.81   91.78   85.81   82.75
   82.45   87.28   92.85   99.97  100.51
   60.59   60.59   60.59   60.59   60.59   60.59   60.59   60.59   60.59   60.59
   60.59   60.59   91.09   91.09   60.59   60.59   60.59   60.59   60.59   60.59
   60.59   60.59   60.59   60.59   60.59
Pier Skew, UpSta & Num, DnSta & Num=  ,4899.3, 2 ,4899.3, 2 , 0 , 0 , 0 ,0,0
     1.5     1.5
   86.68   91.09
     1.5     1.5
   86.43   91.09
Pier Skew, UpSta & Num, DnSta & Num=  ,4932.9, 2 ,4932.9, 2 , 0 , 0 , 0 ,0,0
     1.5     1.5
   80.59   91.09
     1.5     1.5
   80.34   91.09
Pier Skew, UpSta & Num, DnSta & Num=  ,4966.4, 2 ,4966.4, 2 , 0 , 0 , 0 ,0,0
     1.5     1.5
   80.59   91.09
     1.5     1.5
   80.34   91.09
Pier Skew, UpSta & Num, DnSta & Num=  ,5000, 2 ,5000, 2 , 0 , 0 , 0 ,0,0
     1.5     1.5
   80.59   91.09
     1.5     1.5
   80.34   91.09
Pier Skew, UpSta & Num, DnSta & Num=  ,5033.6, 2 ,5033.6, 2 , 0 , 0 , 0 ,0,0
     1.5     1.5
   80.59   91.09
     1.5     1.5
   80.34   91.09
Pier Skew, UpSta & Num, DnSta & Num=  ,5067.1, 2 ,5067.1, 2 , 0 , 0 , 0 ,0,0
     1.5     1.5
   80.59   91.09
     1.5     1.5
   80.34   91.09
Pier Skew, UpSta & Num, DnSta & Num=  ,5100.7, 2 ,5100.7, 2 , 0 , 0 , 0 ,0,0
     1.5     1.5
   86.68   91.09
     1.5     1.5
   86.43   91.09
Abutment Skew #Up #Dn= , 2 , 2
  4882.5    4900
   91.09   86.44
  4882.5    4900
   91.09   86.19
Abutment Skew #Up #Dn= , 2 , 2
    5100  5117.5
   86.44   91.09
    5100  5117.5
   86.19   91.09
BR Coef= 1 , 1 , 0 ,1.25, 0 ,,,0.8,0,2,0,
WSPro=,,,, 1 ,,,, 0 ,,,, 0 ,,,,-1 ,-1 ,-1 , 0 , 0 , 0 , 0 , 0
BC Design=,, 0 ,, 0 ,,,,,,
BC HTab HWMax=95.15
BC Use User HTab Curves=0
BC User HTab FreeFlow(D)= 0

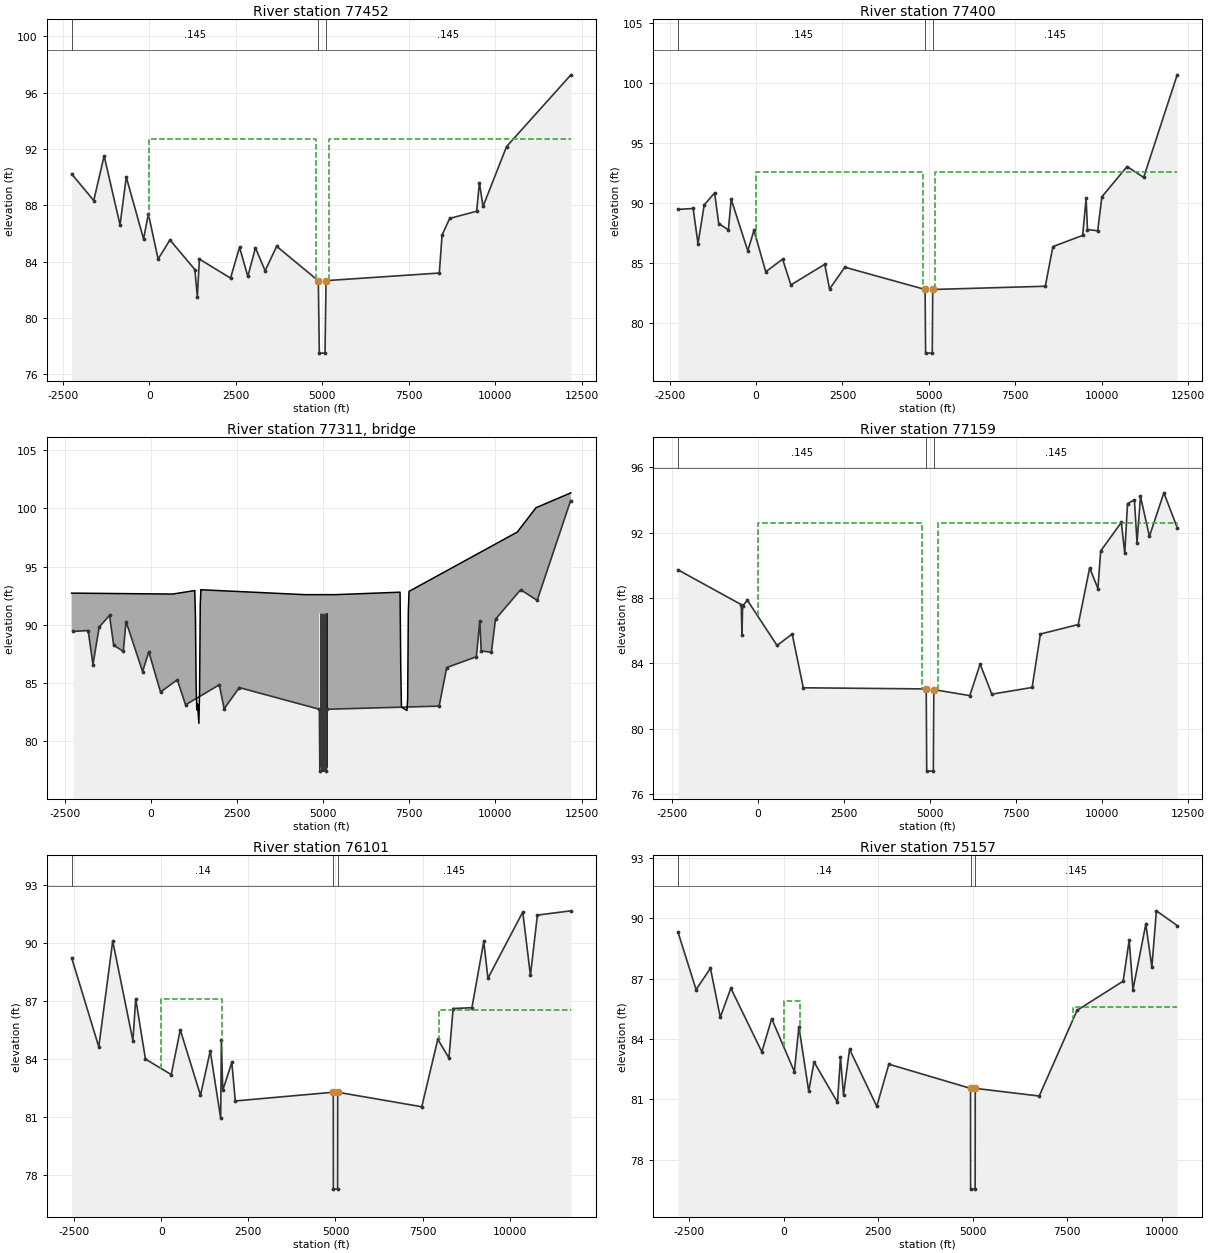
Type RM Length L Ch R = 1 ,77452   ,52,52,52
BEGIN DESCRIPTION:
Highway I-95 South - DS
END DESCRIPTION:
XS GIS Cut Line= 6
       2144761.7       557198.46      2144068.12       554462.32
      2143817.96       553689.46      2141935.93       548781.03
      2140851.47       546043.87      2139856.48       543641.17
#Sta/Elev= 30
 -2244.7   90.23 -1604.7   88.34 -1304.7   91.51  -844.7   86.61  -664.7   90.01
  -164.7   85.61   -24.7   87.39   255.3   84.18     598   85.54    1318   83.44
  1390.3   81.51  1450.3   84.18  2350.3   82.83  2610.3   85.02  2850.3   82.95
  3070.3   84.98  3350.3   83.35  3683.3   85.09  4888.5   82.64  4917.5    77.5
  5082.5    77.5  5111.5   82.65  8387.3   83.19  8467.3   85.89  8687.3   87.07
  9467.3   87.58  9547.3    89.6  9651.4   87.92 10331.4   92.17   12192   97.27
#Mann= 3 ,-1 , 0
 -2244.7    .145       0  4888.5     .05       0  5111.5    .145       0
#XS Ineff= 2 , 0
       0  4809.5   92.69  5190.5       0   92.69
Permanent Ineff=
       F       F
Bank Sta=4888.5,5111.5
XS Rating Curve= 0 ,0
Exp/Cntr=0.5,0.3

Type RM Length L Ch R = 1 ,77400   ,241,241,241
BEGIN DESCRIPTION:
Highway I-95 North - US
END DESCRIPTION:
XS GIS Cut Line= 6
      2144829.82       557182.32       2144106.6       554428.89
      2143851.87       553692.14      2140888.32       545944.37
      2140557.92       545118.38      2139893.33        543630.1
#Sta/Elev= 30
 -2259.8   89.44 -1819.8   89.52 -1679.8   86.58 -1499.8   89.81 -1199.8   90.82
 -1079.8   88.26  -799.8   87.73  -719.8   90.29  -239.8   85.99   -59.8   87.69
   280.2   84.24     767   85.29    1007   83.14  1986.6   84.86  2126.6    82.8
  2566.6   84.62    4890   82.76    4904   77.45    5096   77.45    5110   82.76
  8366.3   83.03  8586.3   86.34  9446.3   87.27  9546.3   90.36  9586.3   87.76
    9882   87.66   10002   90.49 10731.6   93.02 11211.6   92.11 12181.5  100.67
#Mann= 3 ,-1 , 0
 -2259.8    .145       0    4890     .05       0    5110    .145       0
#XS Ineff= 2 , 0
       0    4817    92.6    5183       0    92.6
Permanent Ineff=
       F       F
Bank Sta=4890,5110
XS Rating Curve= 0 ,0
Exp/Cntr=0.5,0.3

Type RM Length L Ch R = 3 ,77311   ,,,
BEGIN DESCRIPTION:
Highway I-95 North - TOR
Structure ID: LDS_FHS_01
Approximate Survey Structure
END DESCRIPTION:
Bridge Culvert--1,0,-1,-1, 0
Deck Dist Width WeirC Skew NumUp NumDn MinLoCord MaxHiCord MaxSubmerge Is_Ogee
70,38,3,0, 28, 28, , , 0.95, 0, 1,1,,
 -2299.3   633.6  1273.6  1293.6  1313.6  1333.6  1353.6  1393.6  1413.6  1433.6
  1453.6  1454.7  4465.4    4887    4887    5113    5113  5364.6    7232    7252
    7272    7432    7452    7472    7492   10633 11175.8 12189.5
   92.73   92.65   92.95   90.76    84.8    82.7   83.21   81.55   84.26   91.74
   93.03   93.02    92.6    92.6    92.6    92.6    92.6    92.6   92.81   86.39
   82.95   82.66   83.59   91.08   92.88   97.97  100.06  101.34
   61.64   61.64   61.64   61.64   61.64   61.64   61.64   61.64   61.64   61.64
   61.64   61.64   61.64   61.64      91      91   61.64   61.64   61.64   61.64
   61.64   61.64   61.64   61.64   61.64   61.64   61.64   61.64
 -2299.3   633.6  1273.6  1293.6  1313.6  1333.6  1353.6  1393.6  1413.6  1433.6
  1453.6  1454.7  4465.4    4887    4887    5113    5113  5364.6    7232    7252
    7272    7432    7452    7472    7492   10633 11175.8 12189.5
   92.73   92.65   92.95   90.76    84.8    82.7   83.21   81.55   84.26   91.74
   93.03   93.02    92.6    92.6    92.6    92.6    92.6    92.6   92.81   86.39
   82.95   82.66   83.59   91.08   92.88   97.97  100.06  101.34
   61.64   61.64   61.64   61.64   61.64   61.64   61.64   61.64   61.64   61.64
   61.64   61.64   61.64   61.64      91      91   61.64   61.64   61.64   61.64
   61.64   61.64   61.64   61.64   61.64   61.64   61.64   61.64
Pier Skew, UpSta & Num, DnSta & Num=  ,4903.1, 2 ,4903.1, 2 , 0 , 0 , 0 ,0,0
     1.5     1.5
   82.41      91
     1.5     1.5
   82.16      91
Pier Skew, UpSta & Num, DnSta & Num=  ,4935.4, 2 ,4935.4, 2 , 0 , 0 , 0 ,0,0
     1.5     1.5
    81.9      91
     1.5     1.5
   81.65      91
Pier Skew, UpSta & Num, DnSta & Num=  ,4967.7, 2 ,4967.7, 2 , 0 , 0 , 0 ,0,0
     1.5     1.5
    81.9      91
     1.5     1.5
   81.65      91
Pier Skew, UpSta & Num, DnSta & Num=  ,5000, 2 ,5000, 2 , 0 , 0 , 0 ,0,0
     1.5     1.5
    81.9      91
     1.5     1.5
   81.65      91
Pier Skew, UpSta & Num, DnSta & Num=  ,5032.3, 2 ,5032.3, 2 , 0 , 0 , 0 ,0,0
     1.5     1.5
    81.9      91
     1.5     1.5
   81.65      91
Pier Skew, UpSta & Num, DnSta & Num=  ,5064.6, 2 ,5064.6, 2 , 0 , 0 , 0 ,0,0
     1.5     1.5
    81.9      91
     1.5     1.5
   81.65      91
Pier Skew, UpSta & Num, DnSta & Num=  ,5096.9, 2 ,5096.9, 2 , 0 , 0 , 0 ,0,0
     1.5     1.5
   82.41      91
     1.5     1.5
   82.16      91
Abutment Skew #Up #Dn= , 2 , 2
    4887  4902.5
      91   82.76
    4887  4902.5
      91   82.51
Abutment Skew #Up #Dn= , 2 , 2
  5097.5    5113
   82.76      91
  5097.5    5113
   82.51      91
BR Coef= 1 , 1 , 0 ,1.25, 0 ,,,0.8,0,2,0,
WSPro=,,,, 1 ,,,, 0 ,,,, 0 ,,,,-1 ,-1 ,-1 , 0 , 0 , 0 , 0 , 0
BC Design=,, 0 ,, 0 ,,,,,,
BC HTab HWMax=100.67
BC Use User HTab Curves=0
BC User HTab FreeFlow(D)= 0

Type RM Length L Ch R = 1 ,77159   ,1058,1058,1058
BEGIN DESCRIPTION:
Highway I-95 North - DS
END DESCRIPTION:
XS GIS Cut Line= 6
      2145082.64       557106.76      2144111.04       553595.64
      2142762.24       550172.65      2141722.35       547389.61
      2140597.19       544577.17      2140037.05       543530.59
#Sta/Elev= 30
 -2325.9   89.72  -485.9   87.59  -465.9   85.73  -445.9   87.52  -305.9   87.85
   554.1   85.09   994.1   85.79  1317.2    82.5    4890   82.43    4904    77.4
    5096    77.4    5110   82.39  6156.3   82.02  6456.3   83.95  6796.3   82.11
  7967.3   82.52  8207.3   85.79  9307.3   86.37  9639.5   89.84  9879.5   88.57
  9959.5   90.87 10559.5   92.62 10659.5   90.73 10739.5   93.77 10939.5      94
 11016.5   91.39 11116.5   94.21 11376.5   91.77 11796.5   94.43 12183.5    92.3
#Mann= 3 ,-1 , 0
 -2325.9    .145       0    4890     .05       0    5110    .145       0
#XS Ineff= 2 , 0
       0    4754    92.6    5246       0    92.6
Permanent Ineff=
       F       F
Bank Sta=4890,5110
XS Rating Curve= 0 ,0
Exp/Cntr=0.5,0.3

Type RM Length L Ch R = 1 ,76101   ,944,944,944
BEGIN DESCRIPTION:
Four Hole Swamp 93.0
END DESCRIPTION:
XS GIS Cut Line= 3
      2145193.73       557000.73      2143606.76       549594.06
        2141939.       543041.03
#Sta/Elev= 30
 -2576.9   89.23 -1796.9   84.63 -1396.9   90.09  -816.9   84.95  -736.9   87.11
  -456.9      84   283.1    83.2   543.1   85.51  1123.1   82.13  1403.1   84.42
  1703.1   80.95  1723.1   84.96  1763.1   82.39  2023.1   83.83  2123.1   81.84
  4937.4   82.29  4939.9   77.29  5060.1   77.29  5062.6   82.29  7477.9   81.54
  7937.9   85.02  8257.9   84.06  8377.9   86.61  8917.9   86.65  9257.9   90.07
  9377.9   88.17 10377.9   91.59 10597.9   88.32 10797.9   91.43 11759.8   91.65
#Mann= 3 ,-1 , 0
 -2576.9     .14       0  4937.4     .05       0  5062.6    .145       0
#XS Ineff= 2 , 0
       0  1734.5    87.1  7961.3       0   86.53
Permanent Ineff=
       F       F
Bank Sta=4937.4,5062.6
XS Rating Curve= 0 ,0
Exp/Cntr=0.3,0.1

Type RM Length L Ch R = 1 ,75157   ,1084,1084,1084
BEGIN DESCRIPTION:
Four Hole Swamp 92.0
END DESCRIPTION:
XS GIS Cut Line= 3
      2145326.06       556909.09      2144442.01       549141.64
      2143611.11       543815.87
#Sta/Elev= 30
 -2802.9   89.31 -2322.9   86.45 -1942.9   87.51 -1682.9   85.08 -1402.9   86.52
  -582.9   83.36  -322.9   85.01   277.1   82.38   397.1   84.61   657.1   81.41
   797.1   82.86  1417.1   80.86  1497.1   83.09  1577.1   81.23  1737.1   83.49
  2457.1   80.66  2777.1   82.75  4937.4   81.55  4939.9   76.55  5060.1   76.55
  5062.6   81.55  6754.7   81.17  7754.7   85.42  8974.7   86.87  9134.7    88.9
  9234.7   86.45  9574.7    89.7  9734.7   87.57  9854.7   90.36 10404.9   89.63
#Mann= 3 ,-1 , 0
 -2802.9     .14       0  4937.4     .05       0  5062.6    .145       0
#XS Ineff= 2 , 0
       0   427.8   85.88  7636.2       0   85.57
Permanent Ineff=
       F       F
Bank Sta=4937.4,5062.6
XS Rating Curve= 0 ,0
Exp/Cntr=0.3,0.1

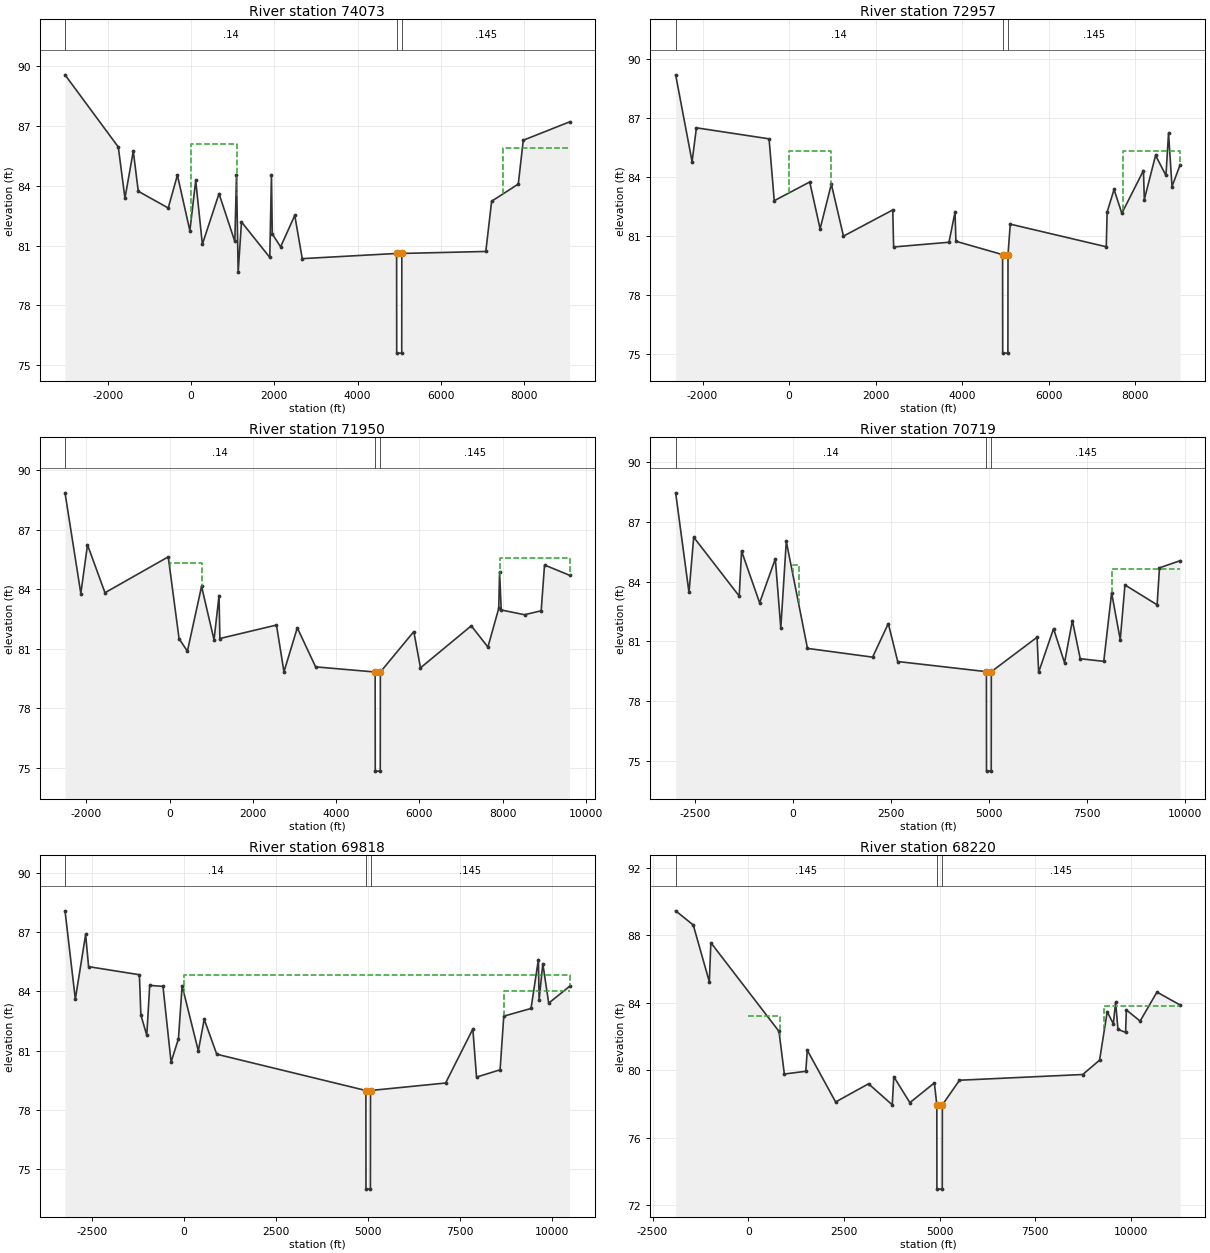
Type RM Length L Ch R = 1 ,74073   ,1116,1116,1116
BEGIN DESCRIPTION:
Four Hole Swamp 91.0
END DESCRIPTION:
XS GIS Cut Line= 3
      2145457.83       556875.97      2145468.66       548845.83
      2144919.14       544790.84
#Sta/Elev= 30
 -3029.6   89.57 -1749.6   85.95 -1589.6   83.38 -1389.6   85.74 -1269.6   83.73
  -549.6   82.89  -329.6   84.54   -29.6   81.75   110.4   84.27   270.4   81.07
   670.4   83.61  1050.4   81.21  1090.4   84.56  1130.4   79.66  1210.4   82.19
  1890.4   80.41  1930.4   84.56  1950.4   81.59  2150.4   80.94  2490.4   82.52
  2670.4   80.35  4937.4   80.61  4939.9   75.61  5060.1   75.61  5062.6   80.61
  7080.6   80.71  7220.6   83.23  7860.6   84.09  7980.6   86.29  9092.6   87.21
#Mann= 3 ,-1 , 0
 -3029.6     .14       0  4937.4     .05       0  5062.6    .145       0
#XS Ineff= 2 , 0
       0    1099    86.1  7499.3       0   85.91
Permanent Ineff=
       F       F
Bank Sta=4937.4,5062.6
XS Rating Curve= 0 ,0
Exp/Cntr=0.3,0.1

Type RM Length L Ch R = 1 ,72957   ,1007,1007,1007
BEGIN DESCRIPTION:
Four Hole Swamp 90.0
END DESCRIPTION:
XS GIS Cut Line= 3
      2145560.21       556868.36      2146477.91       549306.95
      2145459.85       545387.71
#Sta/Elev= 30
 -2622.3   89.19 -2242.3   84.78 -2142.3    86.5  -462.3   85.94  -342.3    82.8
   477.7   83.75   717.7   81.37   977.7   83.64  1257.7      81  2397.7   82.33
  2417.7   80.45  3697.7   80.69  3837.7   82.22  3857.7   80.74  4937.4   80.06
  4939.9   75.06  5060.1   75.06  5062.6   80.06  5114.6   81.61  7334.6   80.46
  7354.6   82.22  7514.6   83.37  7694.6   82.16  8194.6   84.33  8214.6   82.86
  8474.6    85.1  8714.6   84.08  8774.6   86.23  8854.6   83.52  9043.9   84.63
#Mann= 3 ,-1 , 0
 -2622.3     .14       0  4937.4     .05       0  5062.6    .145       0
#XS Ineff= 2 , 0
       0   967.4   85.31  7732.4       0   85.33
Permanent Ineff=
       F       F
Bank Sta=4937.4,5062.6
XS Rating Curve= 0 ,0
Exp/Cntr=0.3,0.1

Type RM Length L Ch R = 1 ,71950   ,1231,1231,1231
BEGIN DESCRIPTION:
Four Hole Swamp 89.0
END DESCRIPTION:
XS GIS Cut Line= 3
      2145621.29       556868.36      2147434.97       549550.56
      2145522.26       545387.65
#Sta/Elev= 30
 -2513.2   88.87 -2133.2   83.79 -1973.2   86.25 -1553.2   83.83   -33.2   85.64
   226.8   81.51   426.8   80.88   766.8   84.15  1066.8   81.45  1186.8   83.69
  1206.8   81.52  2566.8    82.2  2746.8   79.84  3066.8   82.06  3506.8   80.09
  4937.4   79.83  4939.9   74.83  5060.1   74.83  5062.6   79.83    5866   81.87
    6026   80.04    7246   82.16    7646   81.09    7906   83.04    7926   84.87
    7966   82.96    8526   82.72    8926   82.92    9006   85.23  9607.3   84.71
#Mann= 3 ,-1 , 0
 -2513.2     .14       0  4937.4     .05       0  5062.6    .145       0
#XS Ineff= 2 , 0
       0   769.4   85.31  7931.5       0    85.6
Permanent Ineff=
       F       F
Bank Sta=4937.4,5062.6
XS Rating Curve= 0 ,0
Exp/Cntr=0.3,0.1

Type RM Length L Ch R = 1 ,70719   ,901,901,901
BEGIN DESCRIPTION:
Four Hole Swamp 88.0
END DESCRIPTION:
XS GIS Cut Line= 3
      2145664.01       556862.41      2148461.62       549376.55
      2145584.73       545450.15
#Sta/Elev= 30
 -2982.9   88.47 -2642.9   83.46 -2522.9   86.24 -1362.9   83.28 -1302.9   85.54
  -842.9   82.94  -442.9   85.15  -302.9   81.67  -162.9   86.03   377.1   80.65
  2037.1   80.21  2437.1    81.9  2677.1   79.99  4937.4   79.48  4939.9   74.48
  5060.1   74.48  5062.6   79.48  6228.6   81.21  6268.6   79.45  6648.6   81.64
  6928.6   79.93  7128.6   82.05  7328.6   80.13  7928.6      80  8128.6   83.44
  8348.6   81.09  8468.6   83.84  9288.6   82.84  9348.6    84.7  9876.2   85.06
#Mann= 3 ,-1 , 0
 -2982.9     .14       0  4937.4     .05       0  5062.6    .145       0
#XS Ineff= 2 , 0
       0   153.8   84.86  8128.8       0   84.65
Permanent Ineff=
       F       F
Bank Sta=4937.4,5062.6
XS Rating Curve= 0 ,0
Exp/Cntr=0.3,0.1

Type RM Length L Ch R = 1 ,69818   ,1598,1598,1598
BEGIN DESCRIPTION:
Four Hole Swamp 87.0
END DESCRIPTION:
XS GIS Cut Line= 3
      2145699.08       556862.42      2149349.07       549480.96
      2145647.18       545459.08
#Sta/Elev= 30
 -3233.1   88.09 -2953.1   83.61 -2673.1   86.89 -2593.1   85.26 -1213.1   84.85
 -1173.1   82.81 -1013.1   81.78  -933.1   84.31  -573.1   84.26  -353.1   80.42
  -153.1    81.6   -53.1   84.29   386.9   80.99   546.9   82.59   886.9   80.82
  4937.4   78.98  4939.9   73.98  5060.1   73.98  5062.6   78.98  7101.5   79.36
  7841.5    82.1  7941.5   79.66  8581.5   80.03  8681.5   82.75  9421.5   83.14
  9621.5   85.62  9641.5   83.58  9741.5   85.41  9901.5   83.41 10467.7   84.26
#Mann= 3 ,-1 , 0
 -3233.1     .14       0  4937.4     .05       0  5062.6    .145       0
#XS Ineff= 2 , 0
       0   -54.5   84.83  8694.5       0   84.03
Permanent Ineff=
       F       F
Bank Sta=4937.4,5062.6
XS Rating Curve= 0 ,0
Exp/Cntr=0.3,0.1

Type RM Length L Ch R = 1 ,68220   ,1001,1001,1001
BEGIN DESCRIPTION:
Four Hole Swamp 86.0
END DESCRIPTION:
XS GIS Cut Line= 3
      2156215.89       553272.17      2150741.08       549077.85
      2145640.05       545402.99
#Sta/Elev= 30
 -1896.8   89.45 -1436.8   88.61 -1016.8   85.24  -976.8   87.56   803.2    82.3
   943.2   79.77  1503.2   79.93  1543.2   81.18  2283.2   78.11  3143.2   79.19
  3763.2   77.94  3803.2   79.61  4223.2   78.07  4863.2   79.24  4927.7   77.94
  4930.2   72.94  5069.8   72.94  5072.3   77.94    5520    79.4    8740   79.74
    9180   80.59    9380   83.46    9540   82.75    9600   84.04    9660   82.42
    9860   82.24    9880   83.57   10240   82.91   10680   84.63 11286.9   83.86
#Mann= 3 ,-1 , 0
 -1896.8    .145       0  4927.7     .05       0  5072.3    .145       0
#XS Ineff= 2 , 0
       0   819.9    83.2  9305.8       0   83.83
Permanent Ineff=
       F       F
Bank Sta=4927.7,5072.3
XS Rating Curve= 0 ,0
Exp/Cntr=0.3,0.1

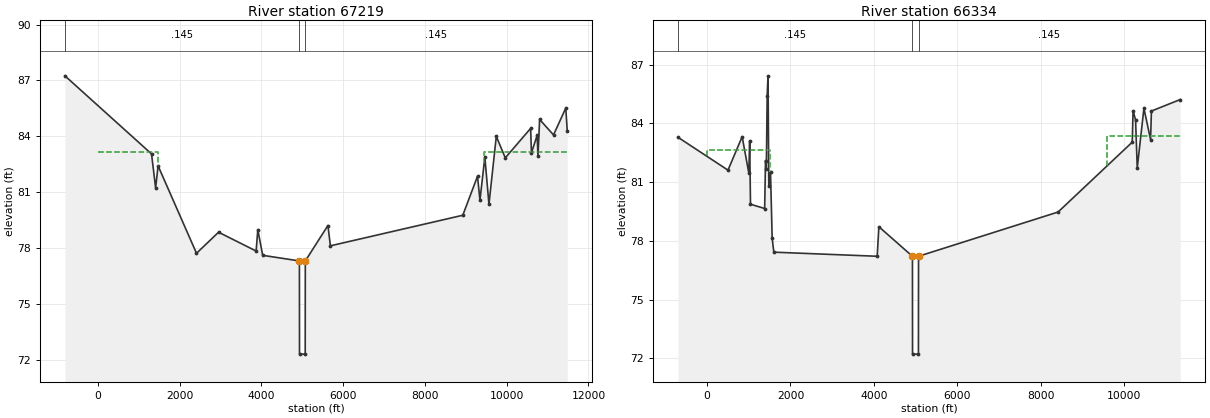
Type RM Length L Ch R = 1 ,67219   ,885,885,885
BEGIN DESCRIPTION:
Four Hole Swamp 85.0
END DESCRIPTION:
XS GIS Cut Line= 3
      2156429.66       551305.99       2151438.8       548397.48
      2145661.71       545384.05
#Sta/Elev= 30
  -810.7   87.25  1309.3   83.06  1409.3   81.23  1469.3   82.42  2409.3   77.73
  2949.3   78.86  3869.3   77.85  3909.3      79  4029.3   77.62  4927.7   77.32
  4930.2   72.32  5069.8   72.32  5072.3   77.32  5625.8   79.22  5685.8   78.13
  8925.8   79.77  9285.8   81.86  9345.8   80.58  9465.8   82.89  9565.8   80.36
  9745.8      84  9965.8   82.85 10585.8   84.43 10605.8   83.12 10745.8   84.06
 10765.8   82.94 10805.8   84.91 11145.8   84.08 11445.8   85.52 11481.6   84.31
#Mann= 3 ,-1 , 0
  -810.7    .145       0  4927.7     .05       0  5072.3    .145       0
#XS Ineff= 2 , 0
       0  1471.3   83.15  9446.1       0   83.18
Permanent Ineff=
       F       F
Bank Sta=4927.7,5072.3
XS Rating Curve= 0 ,0
Exp/Cntr=0.3,0.1

Type RM Length L Ch R = 1 ,66334   ,0,0,0
BEGIN DESCRIPTION:
Four Hole Swamp 84.0
END DESCRIPTION:
XS GIS Cut Line= 3
       2156845.4       549849.46      2151753.65       547569.88
      2145671.53       545354.73
#Sta/Elev= 30
  -698.4   83.29   501.6   81.61   841.6   83.32  1001.6   81.46  1021.6    83.1
  1041.6   79.87  1381.6   79.65  1401.6    82.1  1421.6   81.68  1441.6    85.4
  1461.6   86.43  1481.6   80.78  1521.6   81.51  1561.6   78.13  1601.6   77.42
  4081.6   77.21  4121.6   78.72  4926.9   77.21  4929.4   72.21  5070.6   72.21
  5073.1   77.21  8420.4   79.47 10200.4   83.04 10220.4   84.65 10280.4   84.17
 10320.4   81.72 10480.4   84.77 10640.4   83.17 10660.4   84.63 11353.3   85.22
#Mann= 3 ,-1 , 0
  -698.4    .145       0  4926.9     .05       0  5073.1    .145       0
#XS Ineff= 2 , 0
       0  1520.9   82.64  9590.3       0   83.35
Permanent Ineff=
       F       F
Bank Sta=4926.9,5073.1
XS Rating Curve= 0 ,0
Exp/Cntr=0.3,0.1

Chan Stop Cuts=-1
Use User Specified Reach Order=0
Composite Channel Slope=5

--- SCDOTFEMA.g01 (geometry) ---

Geom Title=Existing Conditions
Program Version=4.10

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
River Reach=Four Hole Swamp ,Reach-1

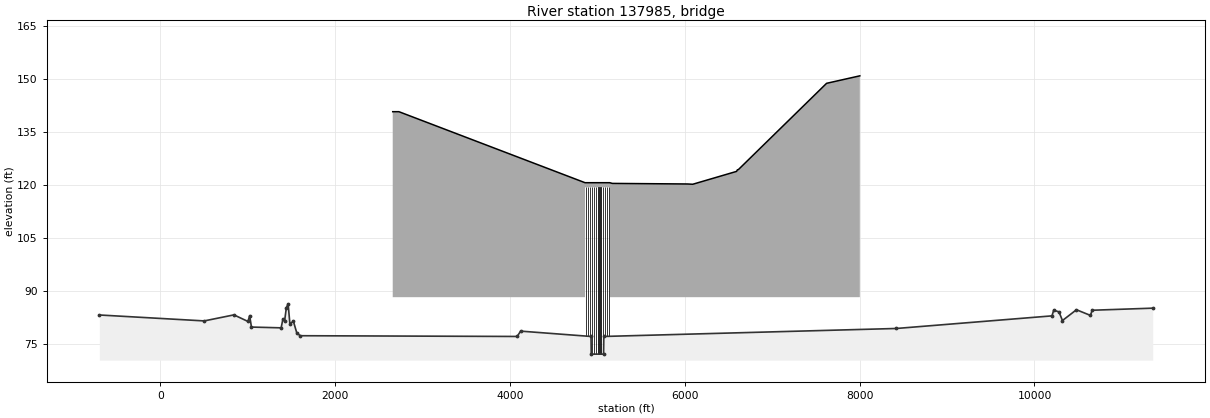
Type RM Length L Ch R = 3 ,137985  ,,,
BEGIN DESCRIPTION:
Five Chop Road - TOR
Structure ID: LDS_FHS_06A
Approximate Survey Structure
END DESCRIPTION:
Bridge Culvert--1,0,-1,-1, 0
Deck Dist Width WeirC Skew NumUp NumDn MinLoCord MaxHiCord MaxSubmerge Is_Ogee
127.5,75,3,0, 14, 14, , , 0.95, 0, 1,1,,
  2658.2  2728.8  4858.5  4858.5  5141.5  5141.5  5170.2  6030.2  6090.2  6591.8
  6601.8  6611.8  7621.8  8002.2
  140.83  140.83  120.73  120.73  120.73  120.73  120.53  120.37  120.29  123.93
   124.4  124.42  148.86  150.98
   88.33   88.33   88.33  119.43  119.43   88.33   88.33   88.33   88.33   88.33
   88.33   88.33   88.33   88.33
  2658.2  2728.8  4858.5  4858.5  5141.5  5141.5  5170.2  6030.2  6090.2  6591.8
  6601.8  6611.8  7621.8  8002.2
  140.83  140.83  120.73  120.73  120.73  120.73  120.53  120.37  120.29  123.93
   124.4  124.42  148.86  150.98
   88.33   88.33   88.33  119.43  119.43   88.33   88.33   88.33   88.33   88.33
   88.33   88.33   88.33   88.33
Pier Skew, UpSta & Num, DnSta & Num=  ,4870.3, 2 ,4870.3, 2 , 0 , 0 , 0 ,0,0
     1.5     1.5
  108.33  119.43
     1.5     1.5
  108.08  119.43
Pier Skew, UpSta & Num, DnSta & Num=  ,4893.9, 2 ,4893.9, 2 , 0 , 0 , 0 ,0,0
     1.5     1.5
  108.33  119.43
     1.5     1.5
  108.08  119.43
Pier Skew, UpSta & Num, DnSta & Num=  ,4917.5, 2 ,4917.5, 2 , 0 , 0 , 0 ,0,0
     1.5     1.5
  108.33  119.43
     1.5     1.5
  108.08  119.43
Pier Skew, UpSta & Num, DnSta & Num=  ,4941, 2 ,4941, 2 , 0 , 0 , 0 ,0,0
     1.5     1.5
  108.33  119.43
     1.5     1.5
  108.08  119.43
Pier Skew, UpSta & Num, DnSta & Num=  ,4964.6, 2 ,4964.6, 2 , 0 , 0 , 0 ,0,0
     1.5     1.5
  108.33  119.43
     1.5     1.5
  108.08  119.43
Pier Skew, UpSta & Num, DnSta & Num=  ,4988.2, 2 ,4988.2, 2 , 0 , 0 , 0 ,0,0
     1.5     1.5
  108.33  119.43
     1.5     1.5
  108.08  119.43
Pier Skew, UpSta & Num, DnSta & Num=  ,5011.8, 2 ,5011.8, 2 , 0 , 0 , 0 ,0,0
     1.5     1.5
  108.33  119.43
     1.5     1.5
  108.08  119.43
Pier Skew, UpSta & Num, DnSta & Num=  ,5035.4, 2 ,5035.4, 2 , 0 , 0 , 0 ,0,0
     1.5     1.5
  108.33  119.43
     1.5     1.5
  108.08  119.43
Pier Skew, UpSta & Num, DnSta & Num=  ,5059, 2 ,5059, 2 , 0 , 0 , 0 ,0,0
     1.5     1.5
  108.33  119.43
     1.5     1.5
  108.08  119.43
Pier Skew, UpSta & Num, DnSta & Num=  ,5082.5, 2 ,5082.5, 2 , 0 , 0 , 0 ,0,0
     1.5     1.5
  108.33  119.43
     1.5     1.5
  108.08  119.43
Pier Skew, UpSta & Num, DnSta & Num=  ,5106.1, 2 ,5106.1, 2 , 0 , 0 , 0 ,0,0
     1.5     1.5
  108.33  119.43
     1.5     1.5
  108.08  119.43
Pier Skew, UpSta & Num, DnSta & Num=  ,5129.7, 2 ,5129.7, 2 , 0 , 0 , 0 ,0,0
     1.5     1.5
  108.33  119.43
     1.5     1.5
  108.08  119.43
Abutment Skew #Up #Dn= , 2 , 2
  4858.5    4870
  119.43  108.33
  4858.5    4870
  119.43  108.08
Abutment Skew #Up #Dn= , 2 , 2
    5130  5141.5
  108.33  119.43
    5130  5141.5
  108.08  119.43
BR Coef= 1 , 1 , 0 ,1.25, 0 ,,,0.8,0,2,0,
WSPro=,,,, 1 ,,,, 0 ,,,, 0 ,,,,-1 ,-1 ,-1 , 0 , 0 , 0 , 0 , 0
BC Design=,, 0 ,, 0 ,,,,,,
BC HTab HWMax=148.63
BC Use User HTab Curves=0
BC User HTab FreeFlow(D)= 0